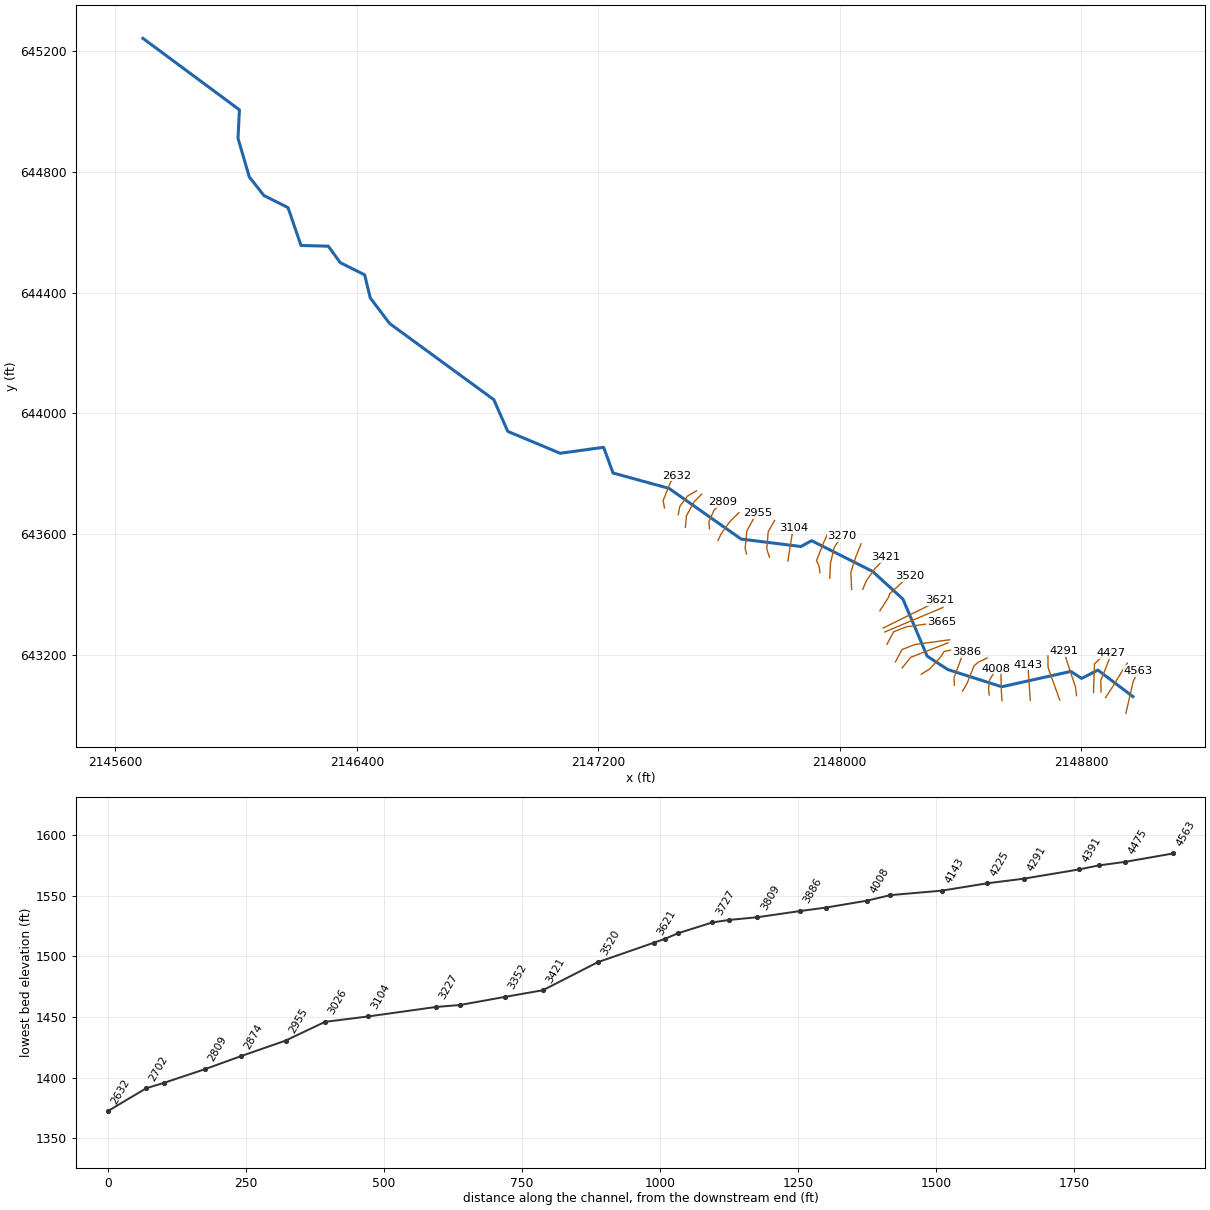
--- CAVERN.prj (project) ---

Proj Title=CAVERN
Current Plan=p01
Default Exp/Contr=0,0
English Units
Geom File=g01
Flow File=f01
Plan File=p01
BEGIN DESCRIPTION:
---------- MODELED AS PART OF WVEMD CTP PROGRAM, 2023----------
Stream Name: Cave Run
Flood Zone:  AFH
Upshur County, WV
HEC-RAS Version: RAS 6.3
Vertical Datum: NAVD88
Projection: NAD 1983 StatePlane West Virginia S FIPS 4702 (US Feet)
Terrain: 1-meter LIDAR (FEMA Region III 3DEP collected 2016-2018)
Land Use: 2019 NLCD
Hydrologic Method:
WV SIR2010-5033 regression equations
Additional Model Notes:
None
END DESCRIPTION:
DSS Export Rating Curves= 0
DSS Export Rating Curve Sorted= 0
DSS Export Volume Flow Curves= 0
DXF OffsetX= 0
DXF OffsetY= 0
DXF ScaleX= 0
DXF ScaleY= 0

--- CAVERN.p01 (plan) ---

Plan Title=Floodplain
Program Version=6.30
Geom File=g01
Flow File=f01
Subcritical Flow
K Sum by GR= 0
Std Step Tol= 0.01
Critical Tol= 0.01
Num of Std Step Trials= 20
Max Error Tol= 0.3
Flow Tol Ratio= 0.001
Split Flow NTrial= 30
Split Flow Tol= 0.02
Split Flow Ratio= 0.02
Log Output Level= 0
Friction Slope Method= 1
Unsteady Friction Slope Method= 2
Unsteady Bridges Friction Slope Method= 1
Parabolic Critical Depth
Global Vel Dist= 0 , 0 , 0
Global Log Level= 0
CheckData=False
Encroach Param=-1 ,0,0, 0
Mapping Interval=1HOUR
Computation Time Step Use Courant=        0
Computation Time Step Use Time Series=    0
Computation Time Step Count To Double=0
Computation Time Step Max Doubling=0
Computation Time Step Max Halving=0
Computation Time Step Residence Courant=0
Run HTab= 0
Run UNet= 0
Run Sediment= 0
Run PostProcess= 0
Run WQNet= 0
Run RASMapper=-1
UNET Theta= 0
UNET Theta Warmup= 0
UNET ZTol= 0
UNET ZSATol= 0
UNET MxIter= 0
UNET Max Iter WO Improvement= 0
UNET MaxInSteps= 0
UNET DtIC= 0
UNET DtMin= 0
UNET MaxCRTS= 0
UNET WFStab= 0
UNET SFStab= 0
UNET WFX= 1
UNET SFX= 1
UNET Gravity=32.17405
UNET 1D Methodology=Finite Difference
UNET DSS MLevel= 1
UNET Pardiso=0
UNET DZMax Abort= 0
UNET Use Existing IB Tables= 0
UNET Froude Reduction=False
UNET Froude Limit= 0
UNET Froude Power= 0
UNET D1 Cores= 0
UNET WindReference=Eulerian
UNET WindDragFormulation=Hsu (1988)
UNET D2 Coriolis=0
UNET D2 Cores= 0
UNET D2 Theta= 1
UNET D2 Theta Warmup= 1
UNET D2 Z Tol= 0.01
UNET D2 Volume Tol= 0.01
UNET D2 Max Iterations= 20
UNET D2 Equation= 0
UNET D2 RampUpFraction=0.1
UNET D2 TimeSlices= 1
UNET D2 Turbulence Formulation=Non-Conservative (original)
UNET D2 Eddy Viscosity=0.3
UNET D2 Transverse Eddy Viscosity=0.1
UNET D2 Smagorinsky Mixing=0
UNET D2 BCVolumeCheck=0
UNET D2 Cores=0
UNET D2 SolverType=PARDISO (Direct)
UNET D2 Minimum Iterations= 3
UNET D2 Maximum Iterations= 30
UNET D2 Restart Number= 10
UNET D2 Relaxation Coeff=1.3
UNET D2 SOR Precondition Iterations= 10
UNET D2 ILUT Maximum Fill= 8
UNET D2 ILUT Tolerance=1E-08
UNET D2 Convergence Tolerance=0.00001
UNET D1D2 MaxIter= 0
UNET D1D2 ZTol=0.01
UNET D1D2 QTol=0.1
UNET D1D2 MinQTol=1
Write IC File= 0
Write IC File at Fixed DateTime=0
Write IC File at Sim End=0
Echo Input=False
Echo Parameters=False
Echo Output=False
Write Detailed= 0
HDF Write Warmup=0
HDF Write Time Slices=0
HDF Flush=0
HDF Compression= 1
HDF Chunk Size= 1
HDF Spatial Parts= 1
HDF Use Max Rows=0
HDF Fixed Rows= 1
Calibration Method= 0
Calibration Iterations= 20
Calibration Max Change=0.05
Calibration Tolerance=0.2
Calibration Maximum=1.5
Calibration Minimum=0.5
Calibration Optimization Method= 1
WQ AD Non Conservative
WQ ULTIMATE=-1
WQ Max Comp Step=1HOUR
WQ Output Interval=15MIN
WQ Output Selected Increments= 0
WQ Output face flow=0
WQ Output face velocity=0
WQ Output face area=0
WQ Output face dispersion=0
WQ Output cell volume=0
WQ Output cell surface area=0
WQ Output cell continuity=0
WQ Output cumulative cell continuity=0
WQ Output face conc=0
WQ Output face dconc_dx=0
WQ Output face courant=0
WQ Output face peclet=0
WQ Output face adv mass=0
WQ Output face disp mass=0
WQ Output cell mass=0
WQ Output cell source sink temp=0
WQ Output nsm pathways=0
WQ Output nsm derived pathways=0
WQ Create Restart=0
WQ Fixed Restart=0
WQ System Summary=0
WQ Write To DSS=0
Sorting and Armoring Iterations= 10
XS Update Threshold= 0.02
Bed Roughness Predictor= 0
Hydraulics Update Threshold= 0.02
Energy Slope Method= 1
Volume Change Method= 1
Sediment Retention Method= 0
Sediment TS Multiplier= 1
Warm Up Method= 0
XS Weighting Method= 0
Number of US Weighted Cross Sections= 1
Number of DS Weighted Cross Sections= 1
Upstream XS Weight=0
Main XS Weight=1
Downstream XS Weight=0
Number of DS XS's Weighted with US Boundary= 1
Upstream Boundary Weight= 1
Weight of XSs Associated with US Boundary= 0
Number of US XS's Weighted with DS Boundary= 1
Downstream Boundary Weight= 0.5
Weight of XSs Associated with DS Boundary= 0.5
Percentile Method= 0
Sediment Output Level= 3
Mass or Volume Output= 0
Output Increment Type= 1
Profile and TS Output Increment= 1
Transport Output Increment 1
XS Output Flag= 0
XS Output Increment= 10
Read HDF5 Sediment Hotstart= 0
Sediment Hotstart Type= 0
Write Gradation File= 0
Read Gradation Hotstart= 0
Write HDF5 File= 1
Write Binary Output= 1
Write DSS Sediment File= 0
DSS Sediment Output Type= 1
SV Curve= 0
Specific Gage Flag= 0
Subcell Erosion Methods= 0
Subcell Deposition Methods= 0
Advection Scheme= 1
Matrix Solver= 0
Implicit Weighting Factor= 1
Maximum Outer Loop Convergence Iterations= 5
Convergence Maximum Absolute= 0.001
Convergence RMSE= 0.0001
Grain Fractions Max Abs Error= 0.001
Max Subgrid Regions= 1
Max Subgrid Length Scale= 3.402823E+38
Initial Layer Thickness= 3.402823E+38
Min Layer Thickness= 3.402823E+38
Max Layer Thickness= 3.402823E+38
Number of Layers= 5

--- CAVERN.f01 (steady flow) ---

Flow Title=Flows
Program Version=6.31
Number of Profiles= 1
Profile Names=01pct
River Rch & RM=CAVERN,Main,4563
     805
Boundary for River Rch & Prof#=CAVERN,Main            , 1
Up Type= 0
Dn Type= 3
Dn Slope=0.03609
DSS Import GetInterval= 0
DSS Import GetPeak= 0
DSS Import FillOption= 0

--- CAVERN.g01 (geometry) ---

Geom Title=Geometry
Program Version=6.30

River Reach=CAVERN          ,Main
Reach XY= 30
     2148971.994      643061.195     2148855.897      643148.961
     2148801.927      643121.375     2148766.242      643144.583
     2148537.168      643093.732     2148358.573      643150.793
      2148290.18      643195.005     2148209.739      643384.217
     2148109.382      643475.989     2147907.007      643577.892
     2147871.808      643558.491      2147673.64      643583.158
     2147434.207      643751.422      2147249.03      643802.045
     2147217.838      643887.2932147073.78608105643867.508065743
     2146900.196      643940.033     2146853.981      644045.198
     2146508.838      644297.423     2146444.537      644382.356
     2146425.937      644458.791     2146345.038      644499.226
     2146305.405      644553.8262146215.07047747644556.133035474
     2146171.995      644681.627     2146092.012      644721.747
2146043.52800057644783.610287512      2146006.22      644911.445
     2146010.942      645005.736     2145691.125      645242.594

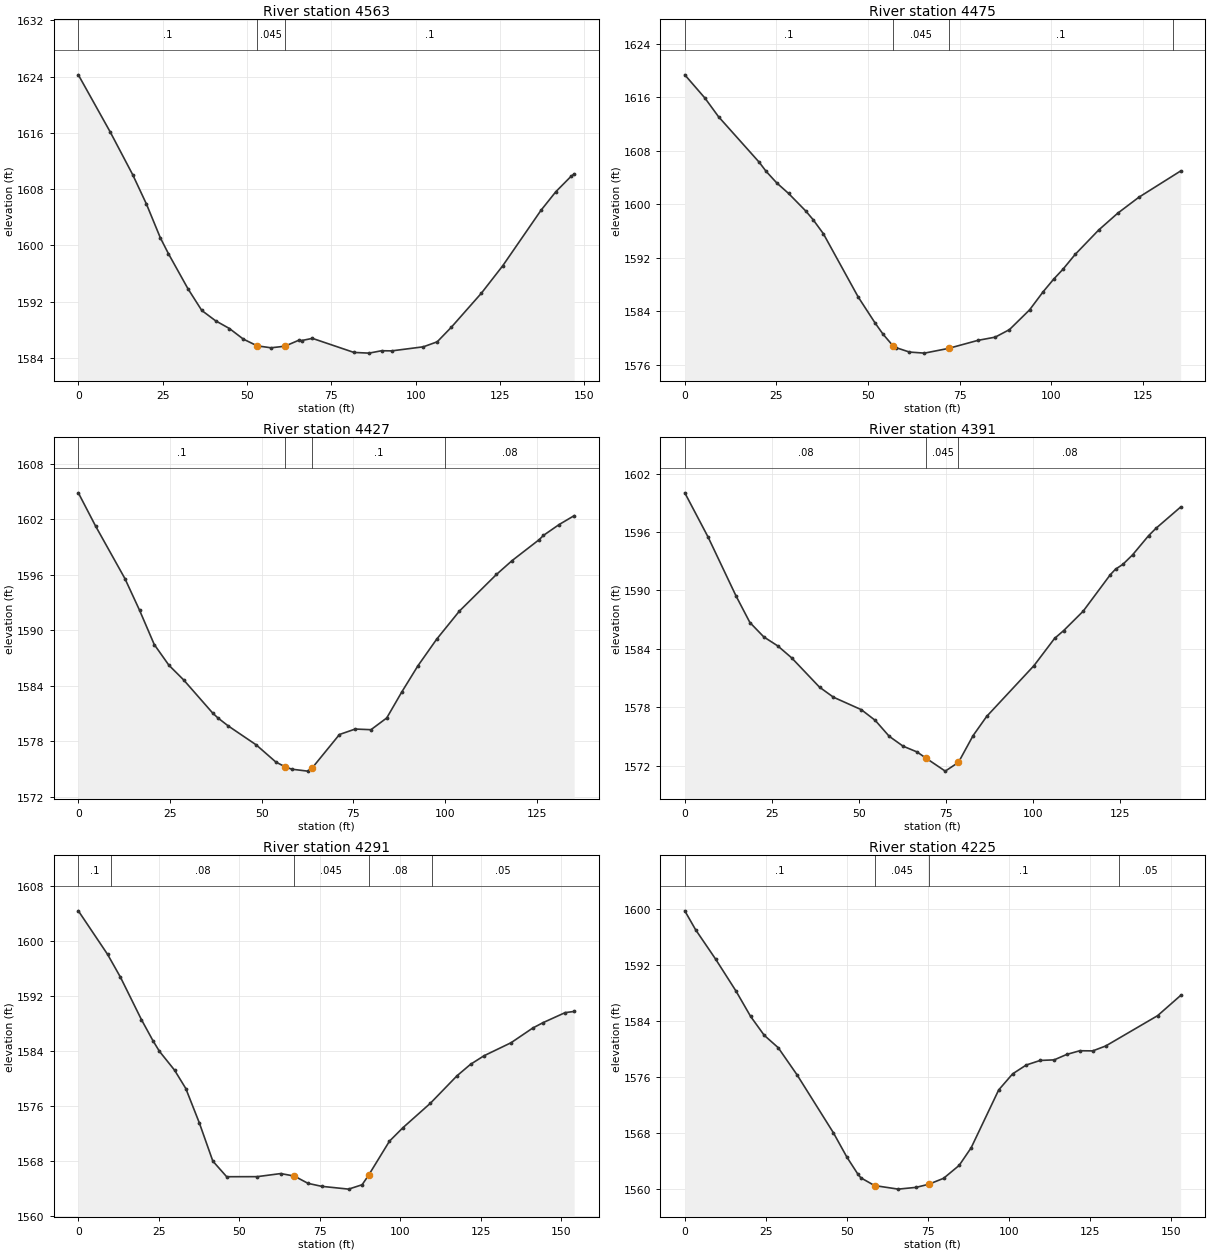
Type RM Length L Ch R = 1 ,4563    ,85.4,87.3,61.1
XS GIS Cut Line= 4
2148948.41126219643005.5422302942148955.94406708 643037.49481009
2148972.86942788643111.6737168082148989.31904597643145.982920252
#Sta/Elev= 30
       0 1624.27     9.5  1616.1    16.1 1610.08    20.2 1605.88    24.3  1601.1
    26.7 1598.84    32.5 1593.84    36.6 1590.75    40.7 1589.28    44.8 1588.18
    48.9 1586.68      53 1585.72    57.1 1585.44    61.2 1585.66    65.3  1586.5
    66.2 1586.47    69.4 1586.78    81.7 1584.78    86.2 1584.68    89.9 1585.02
    92.9    1585   102.3 1585.58   106.4 1586.29   110.6 1588.37   119.5 1593.21
   125.8 1597.09   137.2 1605.02   141.6 1607.66   146.1 1609.84     147 1610.16
#Mann= 3 ,-1,0
       0      .1       0      53    .045       0    61.2      .1       0
Bank Sta=53,61.2
XS Rating Curve= 0 ,0
Exp/Cntr(USF)=0,0
Exp/Cntr=0.3,0.1

Type RM Length L Ch R = 1 ,4475    ,46.9,48.4,49.8
XS GIS Cut Line= 4
2148881.19337013643057.4208054572148905.72680054643095.489921608
2148935.75910328643144.9797726052148953.10170064643172.051144091
#Sta/Elev= 30
       0 1619.35     5.5 1615.87     9.2 1613.09    20.3 1606.28    22.2 1604.91
    25.1 1603.18    28.3 1601.62      33 1598.99      35  1597.7    37.8  1595.6
    47.3 1586.14    51.9 1582.26    54.1 1580.56    56.8 1578.83    57.7 1578.54
    61.3 1577.89    65.4 1577.73      721578.442      80 1579.64    84.7 1580.12
    88.6 1581.25    94.1 1584.21    97.8 1586.92   100.7 1588.82   103.2 1590.28
   106.5 1592.48   112.9 1596.12   118.1 1598.64   123.9 1601.04   135.3 1604.97
#Mann= 4 ,-1,0
       0      .1       0    56.8    .045       0      72      .1       0
  133.18     .08       0
Bank Sta=56.8,72
XS Rating Curve= 0 ,0
Exp/Cntr(USF)=0,0
Exp/Cntr=0.3,0.1

Type RM Length L Ch R = 1 ,4427    ,30.7,35.6,37.8
XS GIS Cut Line= 4
2148866.38871385643076.4553635332148865.54273349643115.370460043
2148881.19337013643153.4395761942148900.65091838643205.044378088
#Sta/Elev= 30
       0 1604.85     4.7 1601.26    12.7 1595.58    16.7 1592.15    20.7 1588.45
    24.7 1586.21    28.7 1584.63    36.7 1581.01    38.1  1580.5    40.9 1579.64
    48.5  1577.6    53.9 1575.73    56.4 1575.23    58.2 1574.97    62.5 1574.76
    63.8 1575.12    71.2 1578.72    75.5 1579.31    79.8 1579.24    84.1 1580.51
    88.2 1583.32    92.6 1586.15    97.7 1589.02   103.9 1592.06     114 1596.02
   118.3 1597.53   125.7  1599.8   126.8 1600.24   131.1 1601.42   135.2 1602.38
#Mann= 4 ,-1,0
       0      .1       0    56.4    .045       0    63.8      .1       0
  100.08     .08       0
Bank Sta=56.4,63.8
XS Rating Curve= 0 ,0
Exp/Cntr(USF)=0,0
Exp/Cntr=0.3,0.1

Type RM Length L Ch R = 1 ,4391    ,87.1,100,99.4
XS GIS Cut Line= 3
2148841.30013772643074.4710068042148844.50010356 643169.55570609
2148878.78545186 643202.01250248
#Sta/Elev= 30
       0 1600.03     6.7 1595.48    14.7 1589.45    18.7 1586.71    22.7 1585.23
    26.7 1584.31    30.7 1583.08    38.7 1580.07    42.7 1579.04    50.7 1577.76
    54.7 1576.66    58.7 1575.03    62.7 1574.01    66.7 1573.42    69.41572.753
    74.8 1571.45    78.61572.352    82.8  1575.1    86.7 1577.07   100.3 1582.29
   106.2 1585.08   108.8 1585.88   114.4 1587.87   122.2 1591.62   123.7 1592.19
   125.8 1592.68   128.6 1593.66   133.2 1595.63   135.3 1596.38   142.4 1598.57
#Mann= 3 ,-1,0
       0     .08       0    69.4    .045       0    78.6     .08       0
Bank Sta=69.4,78.6
XS Rating Curve= 0 ,0
Exp/Cntr(USF)=0,0
Exp/Cntr=0.3,0.1

Type RM Length L Ch R = 1 ,4291    ,65.3,66.5,66.2
XS GIS Cut Line= 4
2148785.17459939643064.1886483282148781.36768778 643093.79796089
2148754.29631629643175.012075347 2148742.7413848643211.924698958
#Sta/Elev= 30
       0 1604.45     9.1 1598.09    13.1 1594.76    19.6 1588.59    23.2  1585.5
    25.2 1583.96    29.9 1581.21    33.4 1578.53    37.6 1573.52    41.8 1567.94
    46.1 1565.66    55.6 1565.67    62.9 1566.12    67.1 1565.76    71.4 1564.69
    75.6 1564.26      84 1563.85    88.2 1564.49    90.2 1565.87    96.7 1570.85
   100.9 1572.82   109.4 1576.37   117.7 1580.39   121.9 1582.06   126.1 1583.31
   134.5 1585.21   141.2 1587.34   144.4 1588.13   151.3  1589.6   154.1 1589.77
#Mann= 5 ,-1,0
       0      .1       0      10     .08       0    67.1    .045       0
    90.2     .08       0  109.85     .05       0
Bank Sta=67.1,90.2
XS Rating Curve= 0 ,0
Exp/Cntr(USF)=0,0
Exp/Cntr=0.3,0.1

Type RM Length L Ch R = 1 ,4225    ,84.4,81.7,76.8
XS GIS Cut Line= 3
2148729.29289679 643050.088975682148690.75379155 643157.24648781
2148690.28380247643196.255582138
#Sta/Elev= 30
       0 1599.69     3.3 1597.02     9.5 1592.81    15.8 1588.25    20.3 1584.64
    24.5 1581.95    28.8 1580.19    34.6 1576.33    45.8 1568.08      50 1564.58
    53.3 1562.22    54.3 1561.64    58.5 1560.54    65.8 1560.03    71.3 1560.28
    75.2 1560.72    79.8 1561.57    84.6 1563.41    88.3 1565.92    96.8 1574.17
   101.1 1576.46   105.3 1577.72   109.6 1578.37   113.9 1578.45   117.8 1579.23
   121.8 1579.75   125.8 1579.73   129.8 1580.43   145.8 1584.75   152.9 1587.63
#Mann= 4 ,-1,0
       0      .1       0    58.5    .045       0    75.2      .1       0
  133.88     .05       0
Bank Sta=58.5,75.2
XS Rating Curve= 0 ,0
Exp/Cntr(USF)=0,0
Exp/Cntr=0.3,0.1

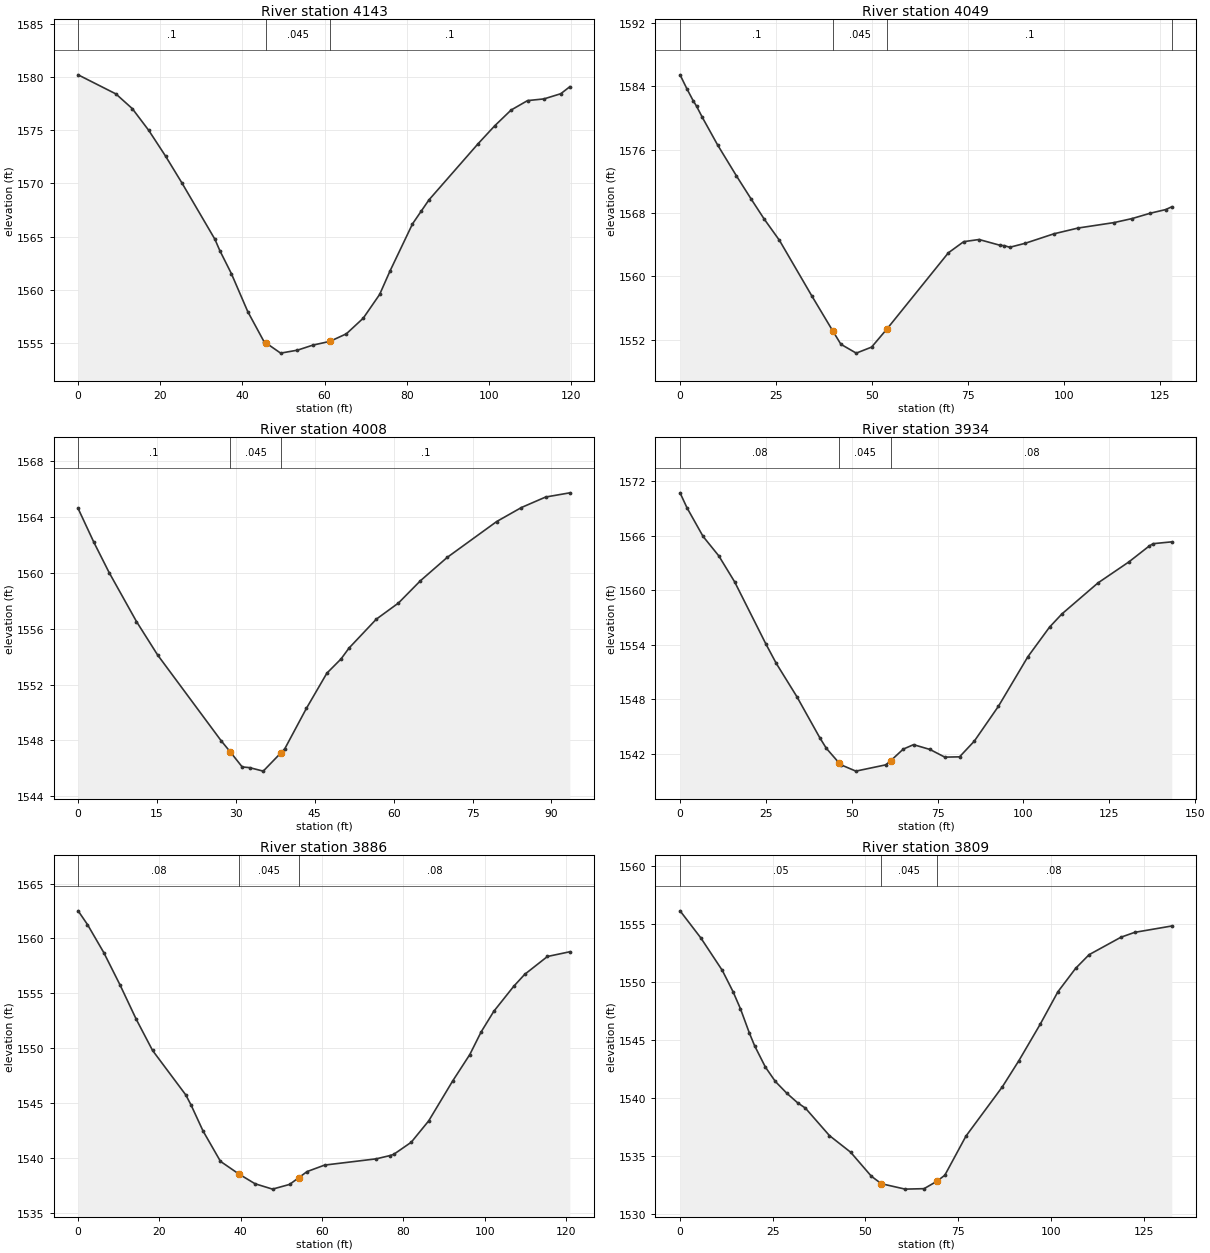
Type RM Length L Ch R = 1 ,4143    ,94,93.8,92.9
XS GIS Cut Line= 2
2148631.66548548643047.9724171942148623.91320256643167.413143171
#Sta/Elev= 30
       0 1580.24     9.2 1578.44    13.2 1577.05    17.2    1575    21.3 1572.57
    25.3 1570.03    33.3 1564.74    34.5 1563.67    37.3 1561.51    41.3 1557.92
    45.3 1555.06    45.8 1554.95    49.3 1554.01    53.4 1554.29    57.1 1554.76
    61.3 1555.12    65.3 1555.83    69.4  1557.3    73.4 1559.54    75.9 1561.73
    81.4 1566.19    83.5 1567.38    85.4 1568.45    97.4 1573.76   101.4 1575.43
   105.4 1576.92   109.4 1577.81   113.4 1577.97   117.5 1578.46   119.7 1579.12
#Mann= 3 ,-1,0
       0      .1       0    45.8    .045       0    61.3      .1       0
Bank Sta=45.8,61.3
XS Rating Curve= 0 ,0
Exp/Cntr(USF)=0,0
Exp/Cntr=0.3,0.1

Type RM Length L Ch R = 1 ,4049    ,42.6,41.1,39.4
XS GIS Cut Line= 5
2148538.01937337643047.359741029 2148535.7352264643081.621945565
2148534.97384407643117.4069147482148534.59315291643139.106310954
2148553.62771099643169.942295037
#Sta/Elev= 30
       0 1585.44     1.8 1583.66     3.4 1582.19     4.3 1581.48     5.8 1580.07
     9.8 1576.57    14.7 1572.67    18.5 1569.77    21.9 1567.24    25.9 1564.53
    34.3 1557.54    39.81553.086    41.9 1551.41    45.9 1550.29    49.9 1551.05
    53.9 1553.34    69.9 1562.96    73.9 1564.37    77.9 1564.64    83.3 1563.92
    84.5 1563.86    85.9 1563.66    89.9 1564.16    97.4 1565.36   103.7 1566.09
   113.1 1566.78   117.8 1567.29   122.5 1567.96   126.5 1568.42   128.1 1568.77
#Mann= 4 ,-1,0
       0      .1       0    39.8    .045       0    53.9      .1       0
  128.07     .08       0
Bank Sta=39.8,53.9
XS Rating Curve= 0 ,0
Exp/Cntr(USF)=0,0
Exp/Cntr=0.3,0.1

Type RM Length L Ch R = 1 ,4008    ,75.6,74.5,70.9
XS GIS Cut Line= 4
2148495.72036811 643066.160605492148493.47242487643085.892551705
2148496.71945399643115.8651282332148519.19888639643153.081077423
#Sta/Elev= 24
       0 1564.58       3 1562.16     5.9    1560    11.1  1556.5    15.1 1554.12
    27.2 1547.98    28.9  1547.2    31.2 1546.11    32.6 1546.06    35.2 1545.81
    38.6 1547.13    39.3 1547.41    43.4 1550.29    47.3 1552.81      50 1553.83
    51.5  1554.6    56.7 1556.67    60.9 1557.82    65.1 1559.42    70.2 1561.09
    79.6 1563.65    84.3 1564.65    88.9  1565.4    93.5  1565.7
#Mann= 3 ,-1,0
       0      .1       0    28.9    .045       0    38.6      .1       0
Bank Sta=28.9,38.6
XS Rating Curve= 0 ,0
Exp/Cntr(USF)=0,0
Exp/Cntr=0.3,0.1

Type RM Length L Ch R = 1 ,3934    ,47.6,48.2,48.2
XS GIS Cut Line= 5
2148407.54395087643079.4433950142148421.64362351643103.465059526
2148445.66528803643163.5192208072148458.72054048643174.485632868
2148489.00872617643189.107515614
#Sta/Elev= 30
       0  1570.7       2 1569.07     6.7 1565.91    11.3 1563.76    15.9 1560.91
      25 1554.08      28 1551.96      34  1548.3    40.7 1543.77    42.6 1542.61
    46.31541.006    46.9 1540.79    51.2  1540.1    59.9 1540.79    61.41541.263
      65 1542.52      68 1543.01    72.8 1542.48    77.1 1541.64    81.4 1541.67
    85.7  1543.4    92.7 1547.22   101.3 1552.68   107.6 1555.93   111.2 1557.38
   121.7 1560.79   130.7  1563.1   136.7 1564.87   137.8 1565.11   143.2 1565.31
#Mann= 3 ,-1,0
       0     .08       0    46.3    .045       0    61.4     .08       0
Bank Sta=46.3,61.4
XS Rating Curve= 0 ,0
Exp/Cntr(USF)=0,0
Exp/Cntr=0.3,0.1

Type RM Length L Ch R = 1 ,3886    ,80.7,76.4,71.2
XS GIS Cut Line= 5
2148380.14071486643098.878180131 2148378.9072755643122.930247715
2148398.02558563643175.0430608152148406.35130133643196.011529991
2148420.22749417643208.654283465
#Sta/Elev= 30
       0 1562.52     2.3 1561.27     6.3 1558.72    10.3 1555.77    14.3 1552.63
    18.3  1549.8    26.5 1545.73    27.8  1544.8    30.7 1542.47      35 1539.69
    39.51538.545    43.5 1537.65    47.8 1537.16      52 1537.59    54.31538.217
    56.3 1538.76    60.6 1539.35    73.3 1539.92    76.7 1540.22    77.6 1540.33
    81.9 1541.43    86.2 1543.38    92.1 1547.02    96.3 1549.42    99.1 1551.49
   102.2 1553.36   107.1 1555.64   109.8 1556.73   115.4 1558.36   120.9 1558.79
#Mann= 3 ,-1,0
       0     .08       0    39.5    .045       0    54.3     .08       0
Bank Sta=39.5,54.3
XS Rating Curve= 0 ,0
Exp/Cntr(USF)=0,0
Exp/Cntr=0.3,0.1

Type RM Length L Ch R = 1 ,3809    ,57.1,51.5,45.4
XS GIS Cut Line= 5
2148270.36461153643135.2646413482148299.04207673643153.149512116
2148334.50345842643192.6195717422148346.52949221643210.812802351
2148369.96484012643215.438199963
#Sta/Elev= 30
       0 1556.16     5.6 1553.82    11.4 1551.01    14.3 1549.17    16.3 1547.69
    18.7  1545.6    20.1 1544.51      23 1542.67    25.7 1541.42    28.8  1540.4
    31.7 1539.58    33.8 1539.12    40.3 1536.74      46 1535.31    51.6 1533.23
    54.31532.587    60.7 1532.12    65.8 1532.16    69.21532.786    71.4 1533.32
    77.1  1536.7    86.9 1540.95    91.4 1543.23    97.1 1546.35   101.9 1549.17
   106.7  1551.2   110.3 1552.37   118.9 1553.88   122.6  1554.3   132.6 1554.85
#Mann= 3 ,-1,0
       0     .05       0    54.3    .045       0    69.2     .08       0
Bank Sta=54.3,69.2
XS Rating Curve= 0 ,0
Exp/Cntr(USF)=0,0
Exp/Cntr=0.3,0.1

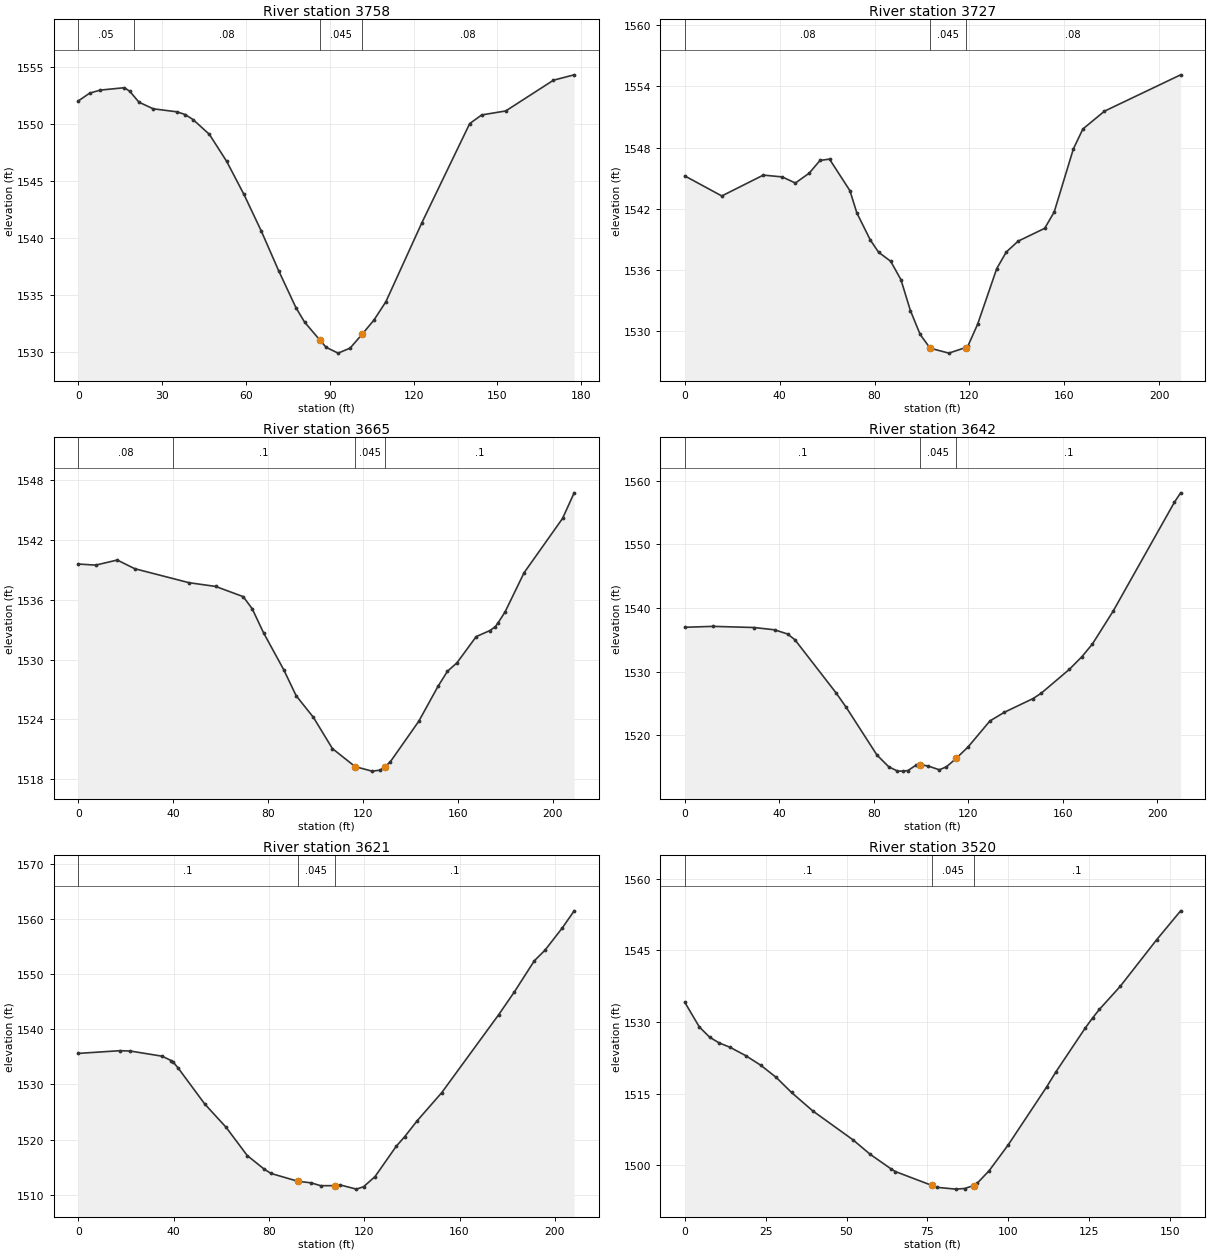
Type RM Length L Ch R = 1 ,3758    ,33.1,30.4,27.4
XS GIS Cut Line= 3
2148207.24976315643156.2987047472148235.59231775643191.498329001
2148359.01957163643239.040678644
#Sta/Elev= 30
       0    1552     4.1 1552.69     7.9 1552.95    16.5 1553.16    18.4 1552.85
    21.7 1551.89    26.8 1551.31    35.4 1551.04    38.3  1550.8    41.1 1550.36
    46.9 1549.07    53.1  1546.7    59.3 1543.79    65.5 1540.58    71.7 1537.11
    77.9 1533.86      81 1532.59    86.51531.007    88.7 1530.38      93 1529.87
    97.3 1530.31   101.61531.532   105.8 1532.76   110.1 1534.38     123 1541.32
   140.1 1550.01   144.4 1550.77     153 1551.12   170.1 1553.82   177.5 1554.29
#Mann= 4 ,-1,0
       0     .05       0      20     .08       0    86.5    .045       0
   101.6     .08       0
Bank Sta=86.5,101.6
XS Rating Curve= 0 ,0
Exp/Cntr(USF)=0,0
Exp/Cntr=0.3,0.1

Type RM Length L Ch R = 1 ,3727    ,62.5,62.6,62.4
XS GIS Cut Line= 4
2148184.85000226643175.9556377722148206.79262517643217.098055732
2148248.84931909643233.5550229162148364.96236533643249.554852123
#Sta/Elev= 30
       0 1545.21    15.6 1543.24    33.1 1545.29    41.1 1545.11    46.6 1544.51
    52.4 1545.47      57 1546.73      61 1546.86    69.6 1543.76    72.5 1541.59
    78.2 1538.91    81.7 1537.71    86.8 1536.82    91.1 1535.02    95.1 1531.98
    99.2 1529.64   103.41528.287   111.3  1527.8   118.41528.349   119.4 1528.53
   123.4 1530.62   131.5 1536.11   135.5 1537.73   140.5  1538.8   151.7 1540.06
   155.7 1541.66   163.8 1547.87   167.8 1549.82   176.9 1551.57     209 1555.14
#Mann= 3 ,-1,0
       0     .08       0   103.4    .045       0   118.4     .08       0
Bank Sta=103.4,118.4
XS Rating Curve= 0 ,0
Exp/Cntr(USF)=0,0
Exp/Cntr=0.3,0.1

Type RM Length L Ch R = 1 ,3665    ,18.9,22.5,25.5
XS GIS Cut Line= 4
2148156.96458565 643234.697867862148178.90720856 643275.84028582
2148220.96390247643292.2972530042148337.07694872643308.297082211
#Sta/Elev= 30
       0 1539.58     7.3 1539.47    16.4 1539.98    23.8 1539.11    46.6 1537.71
    57.9 1537.33    69.5 1536.31    73.3 1535.09    78.1 1532.67    86.6 1528.97
    91.8 1526.38    99.1  1524.2   107.1 1521.07   116.7 1519.26   123.8 1518.81
   127.3 1518.91  129.17 1519.25   131.4 1519.71   143.5 1523.81   151.6 1527.31
   155.6 1528.83   159.6 1529.67   167.7  1532.3   173.5 1532.91   175.8  1533.3
     177 1533.71   179.8 1534.74   187.9 1538.71   204.1 1544.15     209 1546.72
#Mann= 4 ,-1,0
       0     .08       0      40      .1       0   116.7    .045       0
  129.17      .1       0
Bank Sta=116.7,129.17
XS Rating Curve= 0 ,0
Exp/Cntr(USF)=0,0
Exp/Cntr=0.3,0.1

Type RM Length L Ch R = 1 ,3642    ,20.4,21.2,21.9
XS GIS Cut Line= 2
2148149.19324003643275.1545788542148342.56260444 643356.52513882
#Sta/Elev= 30
       0 1536.98    11.9 1537.12    29.3 1536.94      38 1536.58    43.5 1535.92
    46.6 1535.02      64 1526.69    68.3 1524.42    81.3 1516.94    86.3 1515.09
      90 1514.42    92.4 1514.41    94.4  1514.5      98 1515.38    99.5 1515.43
     103 1515.21   107.7 1514.62   110.7 1515.09   114.81516.394   119.9 1518.22
   129.1 1522.28   135.2 1523.64   147.4  1525.8   150.8 1526.63   162.7 1530.37
   168.1 1532.39   172.5 1534.37   181.2 1539.48   207.2 1556.61   209.8 1558.07
#Mann= 3 ,-1,0
       0      .1       0    99.5    .045       0   114.8      .1       0
Bank Sta=99.5,114.8
XS Rating Curve= 0 ,0
Exp/Cntr(USF)=0,0
Exp/Cntr=0.3,0.1

Type RM Length L Ch R = 1 ,3621    ,96.2,101.3,103.6
XS GIS Cut Line= 2
2148144.62186026643288.4115801972148331.13415501643380.753451619
#Sta/Elev= 30
       0 1535.62    17.4 1536.11    21.8 1536.05    35.2 1535.11      39 1534.31
    39.7 1534.11      42 1532.91    53.1 1526.43      62 1522.24    70.9 1517.11
    77.9 1514.69    80.8 1513.88    92.21512.447    97.7 1512.17   101.7 1511.65
   107.61511.661   109.9 1511.79   116.7 1511.03   119.7 1511.46   124.5 1513.29
   133.4 1518.78     137 1520.55   142.3 1523.46   152.5  1528.5   176.4 1542.62
     183 1546.76   191.4 1552.41   195.9 1554.34   203.2  1558.4   208.1 1561.45
#Mann= 3 ,-1,0
       0      .1       0    92.2    .045       0   107.6      .1       0
Bank Sta=92.2,107.6
XS Rating Curve= 0 ,0
Exp/Cntr(USF)=0,0
Exp/Cntr=0.3,0.1

Type RM Length L Ch R = 1 ,3520    ,94.8,99,99.9
XS GIS Cut Line= 5
2148133.27737339 643345.374548852148161.95483859 643390.08672577
2148165.65515668 643401.496039882148190.63230379643424.623027942
2148230.71908309 643461.00948916
#Sta/Elev= 30
       0 1534.12     4.5 1528.96     7.7 1526.81    10.6 1525.63      14  1524.7
    18.8 1522.97    23.5 1520.94    28.3 1518.38      33 1515.24    39.6 1511.37
      52 1505.33    57.3 1502.31    63.7 1499.28    65.1 1498.69    76.3 1495.81
      78 1495.39    83.7 1495.01    86.5 1495.14    89.3 1495.75    90.4 1496.24
    94.1 1498.87     100 1504.28   111.9 1516.43   114.8 1519.62   123.8 1528.73
   126.1 1530.86   128.2 1532.65   134.6 1537.44   145.9 1547.23   153.3 1553.27
#Mann= 3 ,-1,0
       0      .1       0    76.3    .045       0    89.3      .1       0
Bank Sta=76.3,89.3
XS Rating Curve= 0 ,0
Exp/Cntr(USF)=0,0
Exp/Cntr=0.3,0.1

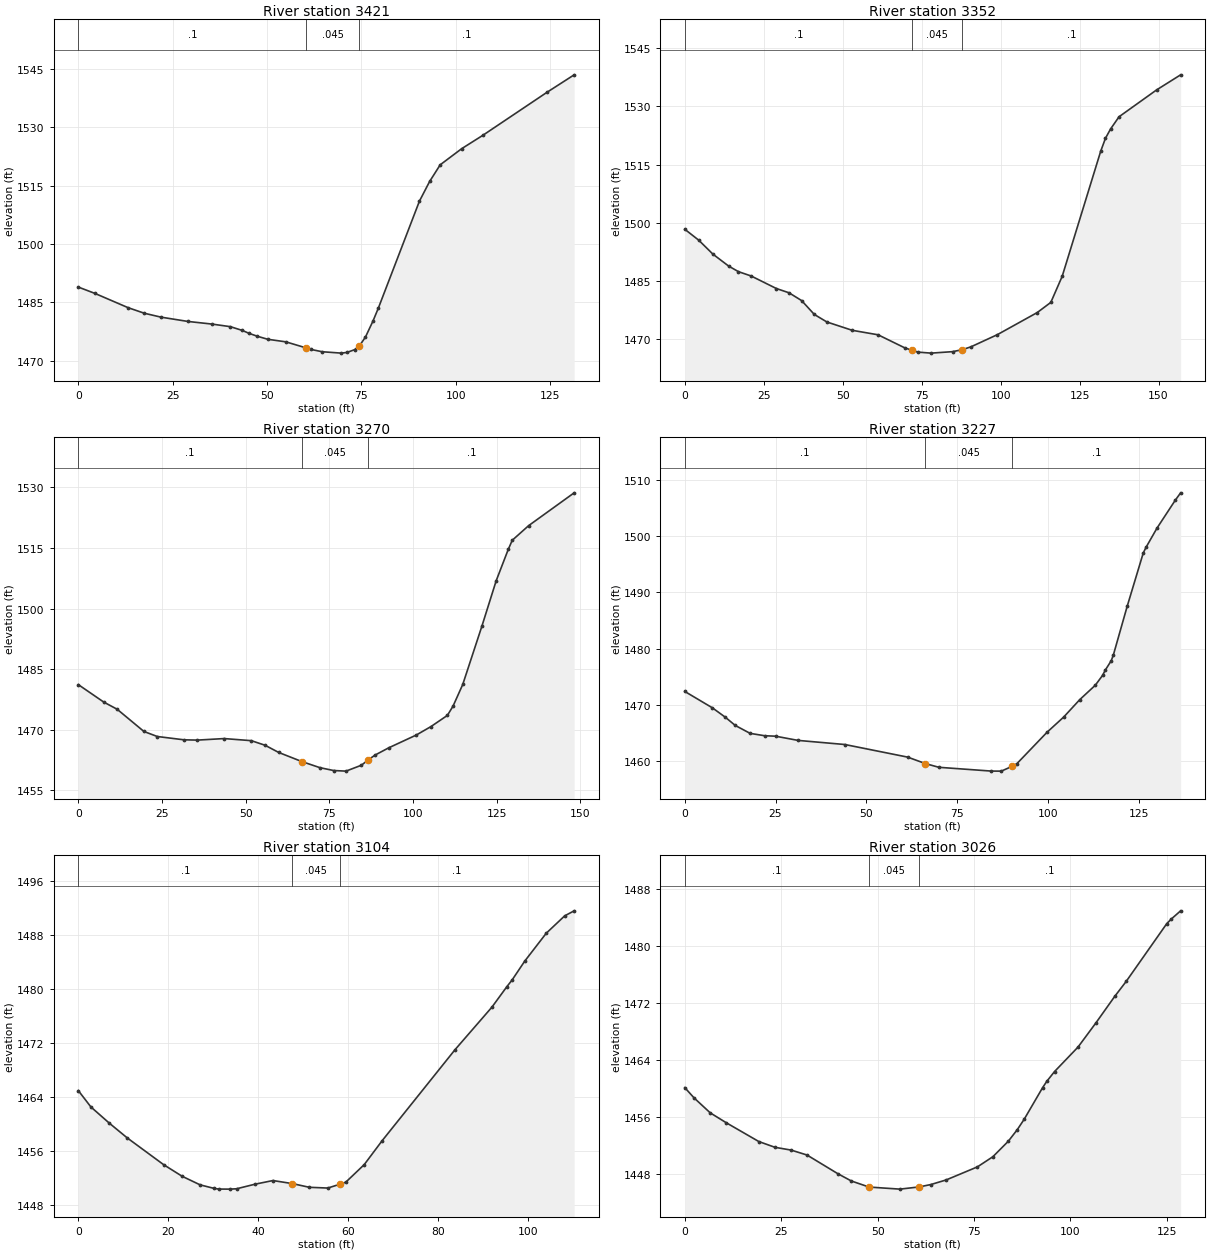
Type RM Length L Ch R = 1 ,3421    ,65.4,69.2,72.8
XS GIS Cut Line= 4
2148076.72095387643417.0957056892148089.05534751643445.773170886
2148118.34953238643487.093389557 2148153.1941944643522.246411411
#Sta/Elev= 30
       0 1488.96     4.4 1487.33    13.2 1483.66    17.5 1482.23    21.9 1481.23
      29 1480.13    35.4 1479.45    40.3 1478.78    43.5  1477.8    45.2 1477.08
    47.4 1476.33    50.2 1475.54      55 1474.88    60.4 1473.31    61.7 1472.92
    64.6 1472.34    69.7 1471.98    71.2 1472.16    73.2 1472.86    74.51473.844
    76.1 1476.13    78.1 1480.26    79.5 1483.53    90.4 1511.06    93.1 1516.11
    95.9 1520.39   101.6 1524.54   107.2 1527.97   124.2 1539.03   131.4 1543.52
#Mann= 3 ,-1,0
       0      .1       0    60.4    .045       0    74.5      .1       0
Bank Sta=60.4,74.5
XS Rating Curve= 0 ,0
Exp/Cntr(USF)=0,0
Exp/Cntr=0.3,0.1

Type RM Length L Ch R = 1 ,3352    ,77.3,81.4,81.4
XS GIS Cut Line= 4
2148039.82900072 643416.240835842148037.25089425643472.908836878
2148053.59396581643524.4049302972148071.02739652643567.238198209
#Sta/Elev= 30
       0 1498.37     4.4 1495.57     8.9 1491.97    13.9 1488.88      17 1487.45
      21 1486.34      29 1483.11      33 1482.01      37    1480      41 1476.44
      45 1474.49      53 1472.35    61.2 1471.19    69.6 1467.85      72 1467.18
    73.8 1466.73      78 1466.47    84.8 1466.85    87.9 1467.37    90.6 1468.09
      99 1471.24   111.6 1476.92   115.9 1479.54   119.5 1486.26   131.7 1518.49
   133.2  1521.8   134.8 1524.18   137.5 1527.35   149.4 1534.27     157 1538.15
#Mann= 3 ,-1,0
       0      .1       0      72    .045       0    87.9      .1       0
Bank Sta=72,87.9
XS Rating Curve= 0 ,0
Exp/Cntr(USF)=0,0
Exp/Cntr=0.3,0.1

Type RM Length L Ch R = 1 ,3270    ,44.8,42.8,40.8
XS GIS Cut Line= 4
2147967.27161288643453.5956630612147969.66996719643503.618481684
2147982.00436083643555.6970325792148007.35839218643592.357591433
#Sta/Elev= 30
       0 1481.19     7.6 1476.87    11.6  1475.1    19.6  1469.6    23.6 1468.35
    31.6 1467.53    35.6 1467.46    43.6 1467.84    51.7 1467.32    55.8 1466.19
    59.9  1464.4    66.8 1462.15    72.2 1460.64    76.3 1459.93      80 1459.78
    84.6 1461.24    86.7 1462.59    88.7 1463.76    92.8 1465.56     101 1468.71
   105.4 1470.81   110.3 1473.57     112 1475.87   114.9 1481.23   120.6  1495.6
   124.9 1506.92   128.5 1514.66   129.7 1516.93   134.6 1520.55   148.2 1528.67
#Mann= 3 ,-1,0
       0      .1       0    66.8    .045       0    86.7      .1       0
Bank Sta=66.8,86.7
XS Rating Curve= 0 ,0
Exp/Cntr(USF)=0,0
Exp/Cntr=0.3,0.1

Type RM Length L Ch R = 1 ,3227    ,106.6,123.5,124
XS GIS Cut Line= 5
2147935.06514061 643471.412009422147931.43976424643495.072381203
 2147923.1973845643511.4068598042147947.78471338643573.307905071
2147959.39130583 643598.52478825
#Sta/Elev= 30
       0 1472.37     7.6 1469.46    11.1 1467.82    13.9 1466.33      18 1464.92
      22  1464.5      25 1464.42    31.2 1463.67    44.1 1462.94    61.4  1460.7
    66.31459.547      70 1458.89    84.4 1458.22    87.2 1458.21    90.21459.067
    91.5 1459.54    99.8 1465.12   104.4 1467.83   108.8 1470.91   113.1 1473.48
   115.1 1475.23   115.9 1476.22   117.5 1477.85   118.1 1478.92   121.9 1487.55
   126.3 1496.97   127.1 1498.02   130.1 1501.41   135.1 1506.33   136.6 1507.67
#Mann= 3 ,-1,0
       0      .1       0    66.3    .045       0    90.2      .1       0
Bank Sta=66.3,90.2
XS Rating Curve= 0 ,0
Exp/Cntr(USF)=0,0
Exp/Cntr=0.3,0.1

Type RM Length L Ch R = 1 ,3104    ,76.6,77.8,78.4
XS GIS Cut Line= 3
2147828.46616126643510.3783514252147841.02896959 643589.56211302
2147845.97795469643619.256023619
#Sta/Elev= 28
       0 1464.95     2.8 1462.53     6.9 1460.13    10.9 1457.94      19 1453.98
    23.1 1452.27    27.1    1451    30.2 1450.48    31.2 1450.38    33.7 1450.37
    35.2 1450.42    39.3  1451.1    43.3 1451.64    47.6 1451.19    51.4 1450.64
    55.5 1450.53    58.1 1451.08    59.5  1451.4    63.6    1454    67.6 1457.55
    83.8 1471.01      92  1477.3    95.3 1480.31    96.5 1481.33    99.3 1484.11
   104.1 1488.25   108.2 1490.82   110.3 1491.56
#Mann= 3 ,-1,0
       0      .1       0    47.6    .045       0    58.1      .1       0
Bank Sta=47.6,58.1
XS Rating Curve= 0 ,0
Exp/Cntr(USF)=0,0
Exp/Cntr=0.3,0.1

Type RM Length L Ch R = 1 ,3026    ,71.7,71.5,71.4
XS GIS Cut Line= 4
2147767.55557542643522.9411597552147758.41898754643550.731614546
2147763.36797264643607.4545976112147784.30598652643644.381640279
#Sta/Elev= 30
       0 1460.16     2.4 1458.72     6.6 1456.62    10.8 1455.22    19.2  1452.6
    23.4 1451.79    27.6  1451.4    31.7 1450.71    39.7 1448.09    43.2 1447.07
    47.8 1446.22    55.8 1445.93    60.8 1446.24    63.8 1446.57    67.8 1447.22
    75.9 1449.05    79.9 1450.47    83.9 1452.64    86.2 1454.24      88  1455.7
    92.8 1460.15    93.9 1461.05    95.9 1462.41     102 1465.85   106.6 1469.21
   111.5 1472.94   114.5 1475.06     125 1483.14   126.2  1483.8   128.6 1484.94
#Mann= 3 ,-1,0
       0      .1       0    47.8    .045       0    60.8      .1       0
Bank Sta=47.8,60.8
XS Rating Curve= 0 ,0
Exp/Cntr(USF)=0,0
Exp/Cntr=0.3,0.1

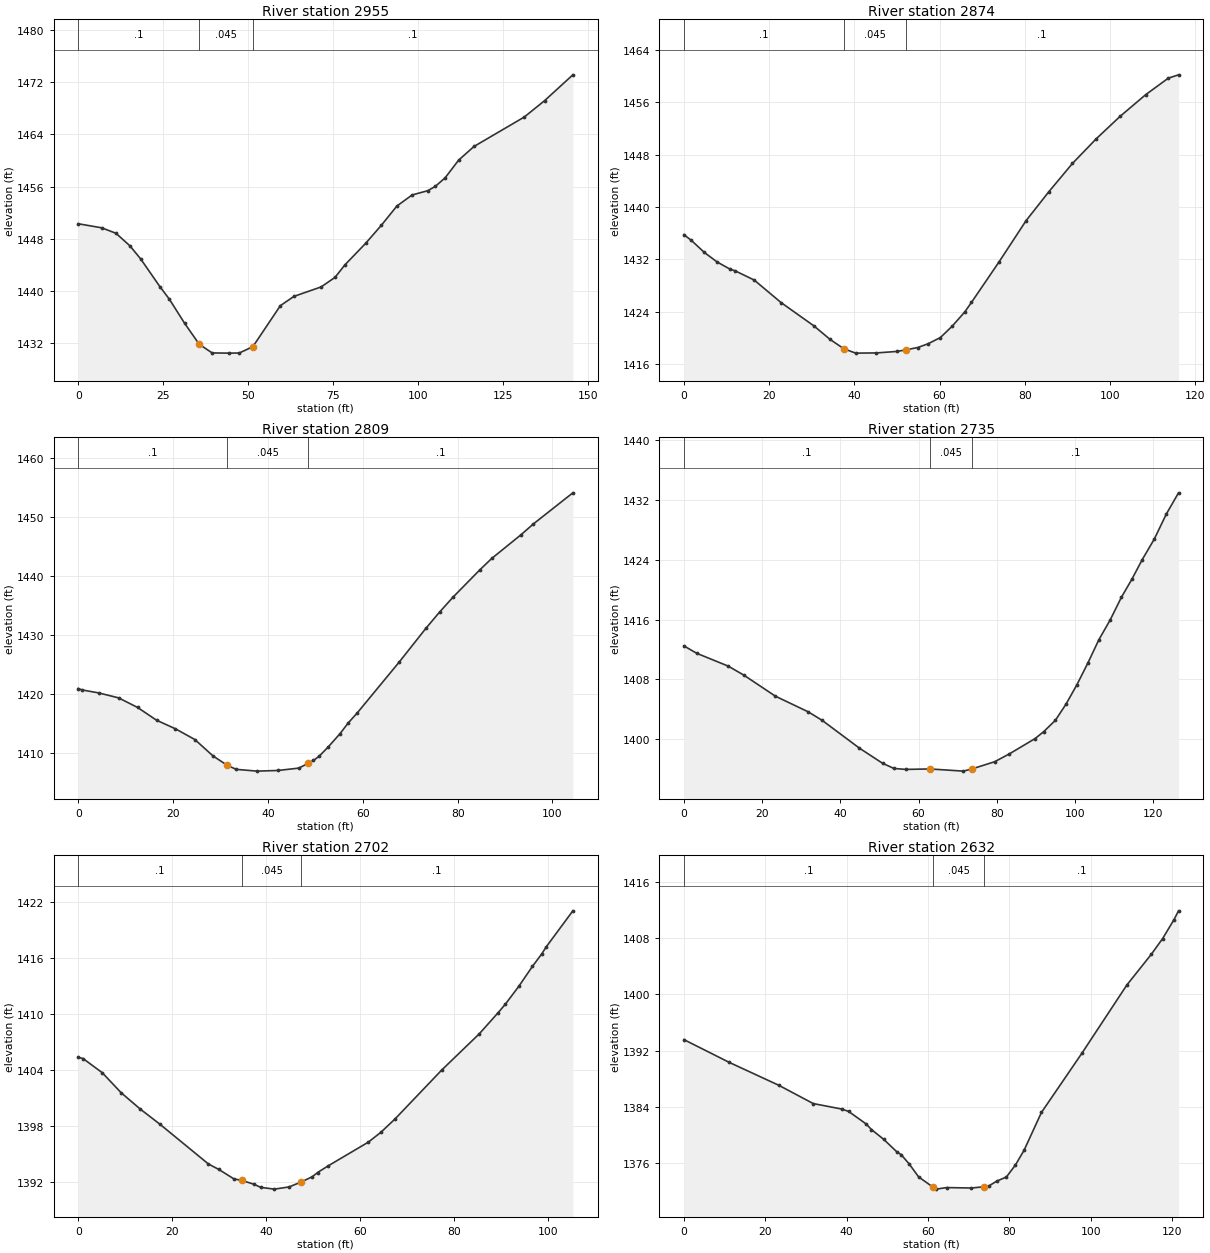
Type RM Length L Ch R = 1 ,2955    ,88.4,80.9,75.2
XS GIS Cut Line= 5
2147691.44661329643534.4700402942147686.84904917643552.254379192
2147692.17872543643609.3580534192147718.82710674643658.086522093
2147727.95984102643669.090695041
#Sta/Elev= 30
       0 1450.31     6.9 1449.69    11.1 1448.85    15.2 1446.93    18.4  1444.9
    24.1 1440.62    26.8 1438.76    31.3 1435.06    35.6 1431.85    39.4 1430.51
    44.5 1430.48    47.4  1430.5    51.4 1431.47    59.5 1437.76    63.5 1439.18
    71.5 1440.63    75.6  1442.1    78.5 1444.01    84.6 1447.31    89.2 1450.06
    93.8 1453.03    98.3 1454.73   102.9 1455.38   105.1 1456.04     108 1457.35
     112 1460.08   116.5 1462.16   131.3 1466.67   137.3 1469.19   145.6 1473.14
#Mann= 3 ,-1,0
       0      .1       0    35.6    .045       0    51.4      .1       0
Bank Sta=35.6,51.4
XS Rating Curve= 0 ,0
Exp/Cntr(USF)=0,0
Exp/Cntr=0.3,0.1

Type RM Length L Ch R = 1 ,2874    ,60.3,64.8,66.1
XS GIS Cut Line= 4
 2147596.8432376643578.1945275582147606.71300845643599.344036531
2147635.85233193643640.7030763012147665.93163358643670.312388863
#Sta/Elev= 30
       0 1435.77     1.7 1434.92     4.8 1433.05     7.8 1431.59    10.8 1430.51
    12.1 1430.22    16.5 1428.83    22.8 1425.39    30.5 1421.83    34.3 1419.76
    37.51418.344    40.3 1417.66    45.2 1417.69      50 1417.92    52.11418.158
    54.9 1418.52    57.3 1419.09    60.2 1420.04      63  1421.8    65.9 1423.94
    67.5 1425.42    73.9 1431.54    80.3  1437.9    85.6 1442.29    91.2 1446.66
    96.8 1450.44   102.4 1453.87   108.4 1457.18   113.7  1459.7   116.1 1460.21
#Mann= 3 ,-1,0
       0      .1       0    37.5    .045       0    52.1      .1       0
Bank Sta=37.5,52.1
XS Rating Curve= 0 ,0
Exp/Cntr(USF)=0,0
Exp/Cntr=0.3,0.1

Type RM Length L Ch R = 1 ,2809    ,74.8,73.9,72.9
XS GIS Cut Line= 4
 2147568.6438923643616.7336327982147566.76393595643640.233087213
2147583.68354313643678.7721924522147612.35287751643704.621592309
#Sta/Elev= 30
       0 1420.97      .8 1420.73     4.3 1420.23     8.5 1419.39    12.5 1417.77
    16.5 1415.61    20.5 1414.15    24.6 1412.33    28.4 1409.57    31.4 1407.98
    33.3 1407.29    37.7 1406.99    42.1  1407.1    46.5  1407.5    48.51408.312
    49.6 1408.79    50.8 1409.52    52.7 1411.07    55.2 1413.33    56.9 1415.12
    58.8 1416.81    67.7 1425.47    73.4 1431.25    76.2 1433.91      79 1436.41
    84.7 1441.07    87.2 1442.99    93.3 1446.95      96 1448.84   104.3 1454.09
#Mann= 3 ,-1,0
       0      .1       0    31.4    .045       0    48.5      .1       0
Bank Sta=31.4,48.5
XS Rating Curve= 0 ,0
Exp/Cntr(USF)=0,0
Exp/Cntr=0.3,0.1

Type RM Length L Ch R = 1 ,2735    ,34.2,32.8,31.3
XS GIS Cut Line= 4
2147488.74574729643621.903512769   2147492.50566643660.442618009
2147517.88507077643706.5015486622147542.32450336643731.880959429
#Sta/Elev= 30
       0 1412.48     3.3 1411.49    11.3 1409.79    15.3 1408.59    23.4 1405.77
    31.8 1403.68    35.4 1402.53    44.9 1398.83    50.8 1396.82    53.7 1396.13
    56.7    1396    62.9 1396.06    71.5 1395.77    73.81396.085    79.5 1397.03
    83.2 1398.06    89.8 1400.11      92 1401.03      95 1402.55    97.7 1404.69
   100.5 1407.29   103.3 1410.18   106.1 1413.28     109 1415.93   111.9 1418.98
   114.6 1421.41   117.2 1423.98   120.3 1426.74   123.4  1430.1   126.5 1432.91
#Mann= 3 ,-1,0
       0      .1       0    62.9    .045       0    73.8      .1       0
Bank Sta=62.9,73.8
XS Rating Curve= 0 ,0
Exp/Cntr(USF)=0,0
Exp/Cntr=0.3,0.1

Type RM Length L Ch R = 1 ,2702    ,65.3,69.9,71.2
XS GIS Cut Line= 4
2147465.24629288643664.2025307162147470.41617285643691.461897836
2147495.59508316643725.5804562812147525.87488527643743.160697548
#Sta/Elev= 30
       0 1405.37       1 1405.24     5.1 1403.72     9.1 1401.58    13.2 1399.81
    17.3 1398.22    27.7 1393.92    29.9 1393.34    33.1 1392.33    34.8 1392.16
    37.4 1391.75    38.8 1391.42    41.7 1391.23    44.8 1391.46    47.4 1391.99
    49.8 1392.57    50.9 1393.01    53.1 1393.71    61.7 1396.27    64.4 1397.34
    67.4 1398.77    77.3    1404    85.3 1407.89    89.3 1410.15    90.8 1411.04
    93.7 1412.98    96.6 1415.12    98.6 1416.47    99.5 1417.19   105.2 1421.08
#Mann= 3 ,-1,0
       0      .1       0    34.8    .045       0    47.4      .1       0
Bank Sta=34.8,47.4
XS Rating Curve= 0 ,0
Exp/Cntr(USF)=0,0
Exp/Cntr=0.3,0.1

Type RM Length L Ch R = 1 ,2632    ,63.6,67.8,69.8
XS GIS Cut Line= 4
2147419.65735131643686.2920178652147414.95746043643710.731450456
2147440.16978748643773.119396333 2147461.3096705643793.603779105
#Sta/Elev= 30
       0 1393.57    11.1 1390.34    23.3 1387.08    31.8 1384.47    38.8 1383.69
    40.5 1383.35    44.8 1381.57    46.1 1380.78    49.1 1379.39    52.3 1377.63
    53.4 1377.21    55.4 1375.87    57.7 1374.04    61.21372.598      62  1372.3
    64.6 1372.52    70.7 1372.46    73.8 1372.64      75 1372.77    76.9 1373.43
    79.3 1374.04    81.5 1375.73    83.6  1377.8    87.9 1383.21    97.9 1391.68
   108.9 1401.34   114.9  1405.7   117.7 1407.95   120.5 1410.65   121.6 1411.89
#Mann= 3 ,-1,0
       0      .1       0    61.2    .045       0    73.8      .1       0
Bank Sta=61.2,73.8
XS Rating Curve= 0 ,0
Exp/Cntr(USF)=0,0
Exp/Cntr=0.3,0.1