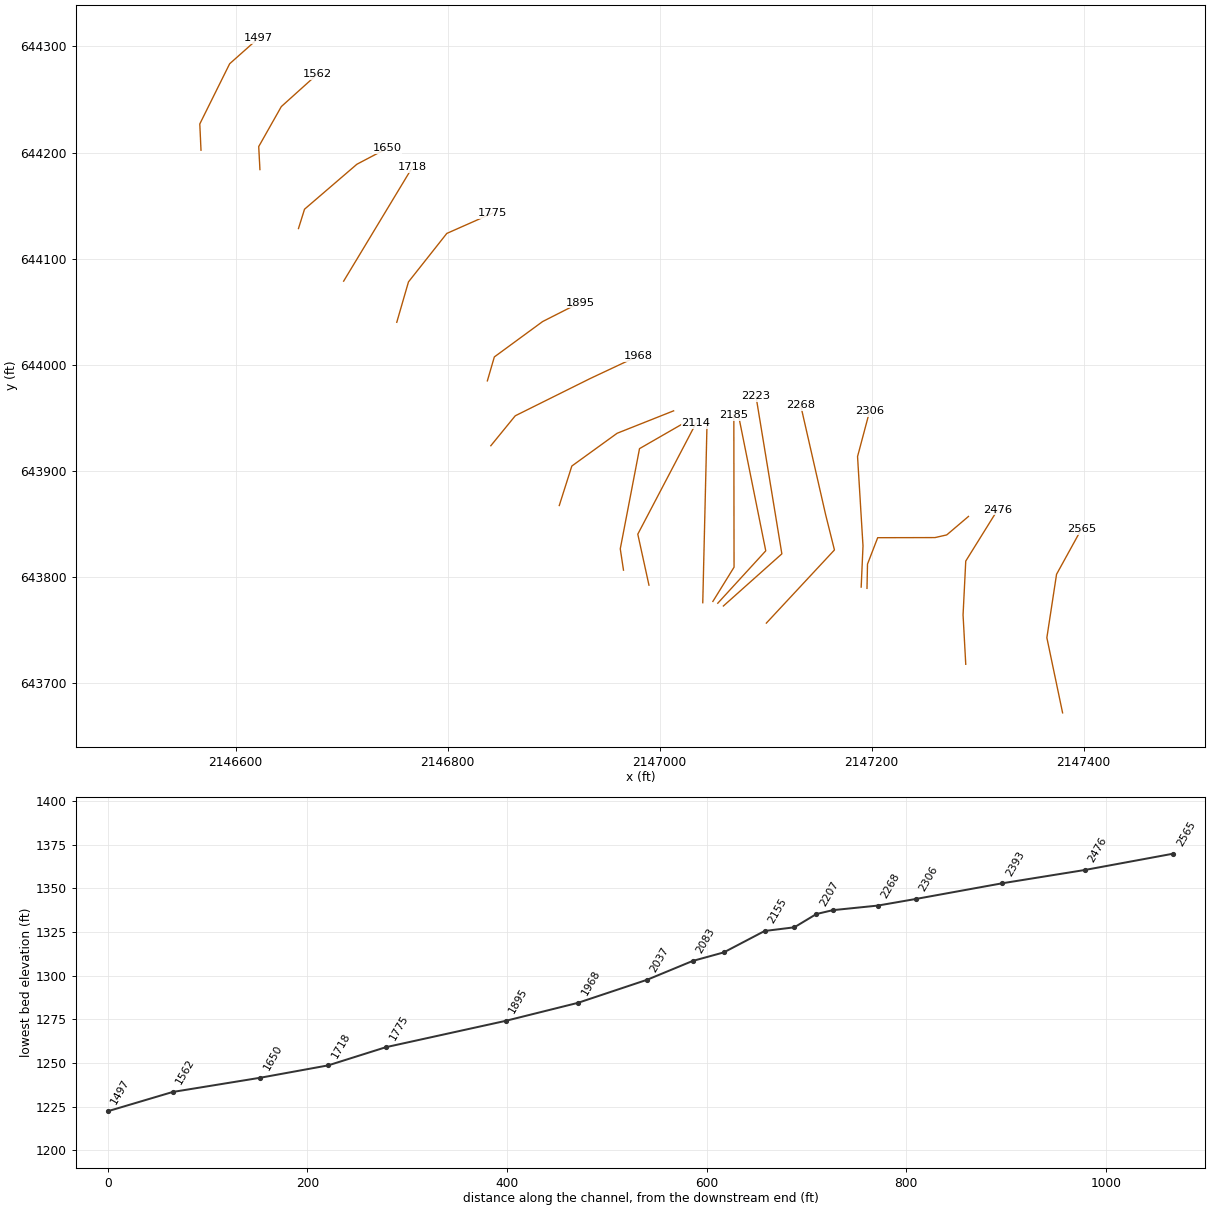
HEC-RAS study CAVERN.prj: CAVERN

--- CAVERN.g01 (geometry) --- (continued)

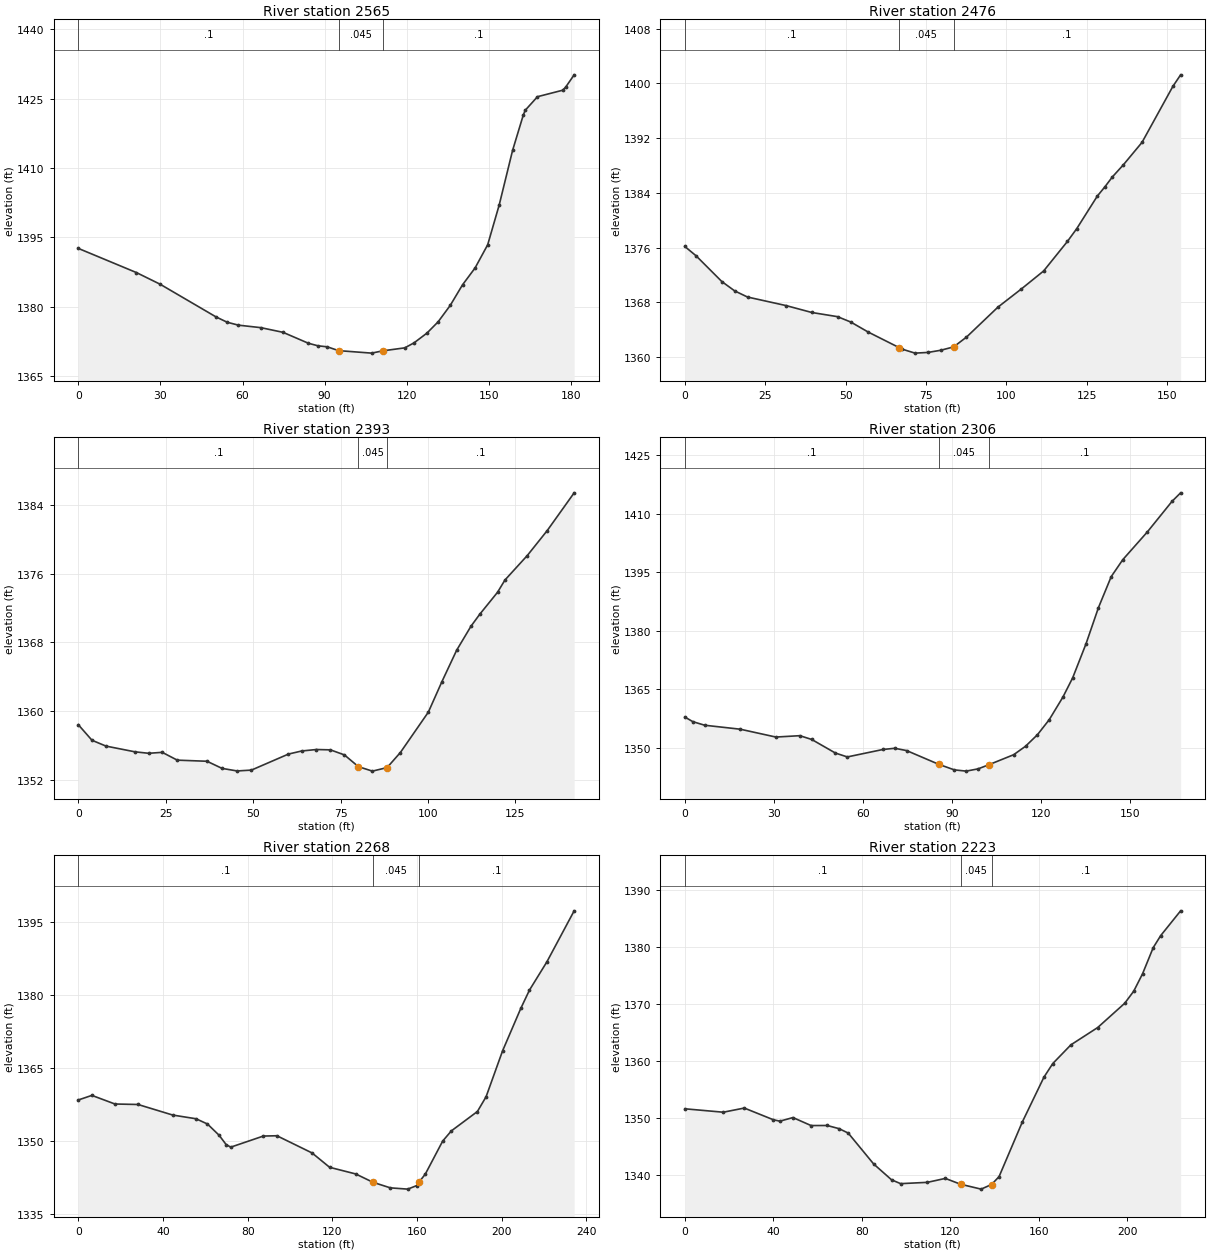
Type RM Length L Ch R = 1 ,2565    ,87.8,88.8,90.3
XS GIS Cut Line= 4
2147380.05415276643671.9256480122147365.20719746643742.734204054
2147374.34378533643802.5027164122147397.68553172643844.877841146
#Sta/Elev= 30
       0 1392.59    21.2 1387.37    29.9 1384.84    50.3 1377.78    54.4 1376.62
    58.5 1375.99    66.7 1375.45    74.8 1374.44    84.1 1372.07    87.6 1371.52
      91  1371.3    95.1 1370.48   107.2 1369.94   111.2 1370.43   119.3 1371.08
   122.7 1372.17   127.4 1374.27   131.5 1376.72   135.9 1380.25   140.4 1384.71
     145 1388.37   149.6 1393.38   153.8 1401.97   158.7 1413.79   162.6 1421.41
   163.3 1422.45   167.8  1425.4     177  1426.8   178.1 1427.47   181.2 1430.13
#Mann= 3 ,-1,0
       0      .1       0    95.1    .045       0   111.2      .1       0
Bank Sta=95.1,111.2
XS Rating Curve= 0 ,0
Exp/Cntr(USF)=0,0
Exp/Cntr=0.3,0.1

Type RM Length L Ch R = 1 ,2476    ,94.8,82.5,60.2
XS GIS Cut Line= 4
2147288.70195129643717.7027751982147286.16401021643764.231694939
2147288.70195129643814.9905164752147318.73425403643863.211396933
#Sta/Elev= 29
       0 1376.16     3.5  1374.8    11.5 1371.04    15.5 1369.67    19.5 1368.77
    31.5 1367.52    39.5 1366.51    47.5  1365.9    51.6 1365.12      57 1363.66
    66.6 1361.39    67.6 1361.15    71.6 1360.57    75.6 1360.67    79.6 1360.99
    83.6 1361.48    87.6 1362.91    97.4  1367.3   104.7 1369.96   111.6 1372.58
     119  1376.9   121.9 1378.77   128.3 1383.53   130.6 1384.85     133 1386.34
   136.4  1388.1   142.2 1391.38   151.8 1399.57   154.2 1401.25
#Mann= 3 ,-1,0
       0      .1       0    66.6    .045       0    83.6      .1       0
Bank Sta=66.6,83.6
XS Rating Curve= 0 ,0
Exp/Cntr(USF)=0,0
Exp/Cntr=0.3,0.1

Type RM Length L Ch R = 1 ,2393    ,66.1,86.7,103.1
XS GIS Cut Line= 6
2147195.54906718 643789.27761945 2147196.0283717643812.140346903
2147205.63983461643837.0089475722147259.72009683 643837.11749401
2147270.75525713643839.631548018 2147291.2614949643857.040619552
#Sta/Elev= 30
       0 1358.39     3.9 1356.58     7.9  1355.9    16.2 1355.23    20.1 1355.06
      24 1355.17    28.3 1354.26    36.8 1354.13    41.1  1353.3    45.4    1353
    49.5  1353.1    60.1 1354.97    63.9 1355.33    68.1  1355.5    72.1 1355.46
    76.1 1354.87    80.1  1353.5    84.1 1352.98    88.31353.393    92.1 1355.15
   100.1 1359.86     104 1363.43   108.2 1367.08   112.3 1369.88   114.8 1371.27
   119.9 1373.84     122 1375.26   128.4 1378.12   134.1 1381.03   141.8 1385.43
#Mann= 3 ,-1,0
       0      .1       0    80.1    .045       0    88.3      .1       0
Bank Sta=80.1,88.3
XS Rating Curve= 0 ,0
Exp/Cntr(USF)=0,0
Exp/Cntr=0.3,0.1

Type RM Length L Ch R = 1 ,2306    ,34.7,38.2,39.5
XS GIS Cut Line= 4
 2147190.0657981 643790.462625112147191.77890832643829.178916237
2147186.63957764643913.4639393962147197.94610514643955.949073022
#Sta/Elev= 30
       0 1357.86     2.7 1356.67     6.7 1355.75    18.7 1354.73    30.7 1352.72
    38.8 1353.07    42.8  1352.1    50.8 1348.61    54.8 1347.62    66.8 1349.53
    70.8 1349.84    74.8 1349.25    85.71345.705    90.9  1344.3    94.9 1343.98
    98.9 1344.56   102.6 1345.64   110.9 1348.19   114.9 1350.36   118.9  1353.3
   122.9 1357.18   127.5 1362.96   130.8 1367.91   135.3 1376.64   139.5 1385.93
   143.8 1393.87   147.7 1398.21     156 1405.34   164.3 1413.16   167.2 1415.35
#Mann= 3 ,-1,0
       0      .1       0    85.7    .045       0   102.6      .1       0
Bank Sta=85.7,102.6
XS Rating Curve= 0 ,0
Exp/Cntr(USF)=0,0
Exp/Cntr=0.3,0.1

Type RM Length L Ch R = 1 ,2268    ,47.2,45.1,44.9
XS GIS Cut Line= 4
2147100.61520314643756.5253870712147164.84704521 643825.45712002
2147156.49168364643858.8785662982147132.99222922643961.753955623
#Sta/Elev= 30
       0 1358.49     6.4 1359.43    17.3 1357.66    28.2 1357.56    44.6 1355.39
    55.6 1354.63      61 1353.55    66.5 1351.24    69.8 1349.34      72  1348.8
    87.4 1351.08    93.8 1351.14   110.4 1347.61   118.7 1344.66     131  1343.3
   139.2 1341.58   147.4 1340.44   155.6 1340.18   159.8  1340.9   160.9 1341.61
   163.9 1343.27   172.1 1350.05   176.2 1352.14   188.5 1356.12   192.6 1359.15
   200.4 1368.59     209  1377.3   213.1 1381.06   221.3 1386.84   234.2 1397.33
#Mann= 3 ,-1,0
       0      .1       0   139.2    .045       0   160.9      .1       0
Bank Sta=139.2,160.9
XS Rating Curve= 0 ,0
Exp/Cntr(USF)=0,0
Exp/Cntr=0.3,0.1

Type RM Length L Ch R = 1 ,2223    ,16,16.5,17
XS GIS Cut Line= 3
2147060.10043246643772.6512240152147115.23708589643821.801649333
2147090.84803227643970.167491006
#Sta/Elev= 30
       0 1351.65    17.4 1351.05    26.9 1351.78    40.1 1349.72      43 1349.48
    48.9 1350.11    57.1 1348.71    64.4 1348.72    69.8 1348.16    73.9 1347.39
    85.4 1341.97    93.5 1339.19    97.6 1338.52   109.7 1338.75   117.8 1339.44
   124.7 1338.42     134 1337.56   138.7 1338.37   142.1 1339.75   152.6 1349.32
   162.4  1357.2   166.4 1359.59   174.6 1362.87   186.7  1365.9   198.9 1370.15
     203 1372.28     207 1375.34   211.8 1379.91   215.2 1382.03   224.2 1386.37
#Mann= 3 ,-1,0
       0      .1       0   124.7    .045       0   138.7      .1       0
Bank Sta=124.7,138.7
XS Rating Curve= 0 ,0
Exp/Cntr(USF)=0,0
Exp/Cntr=0.3,0.1

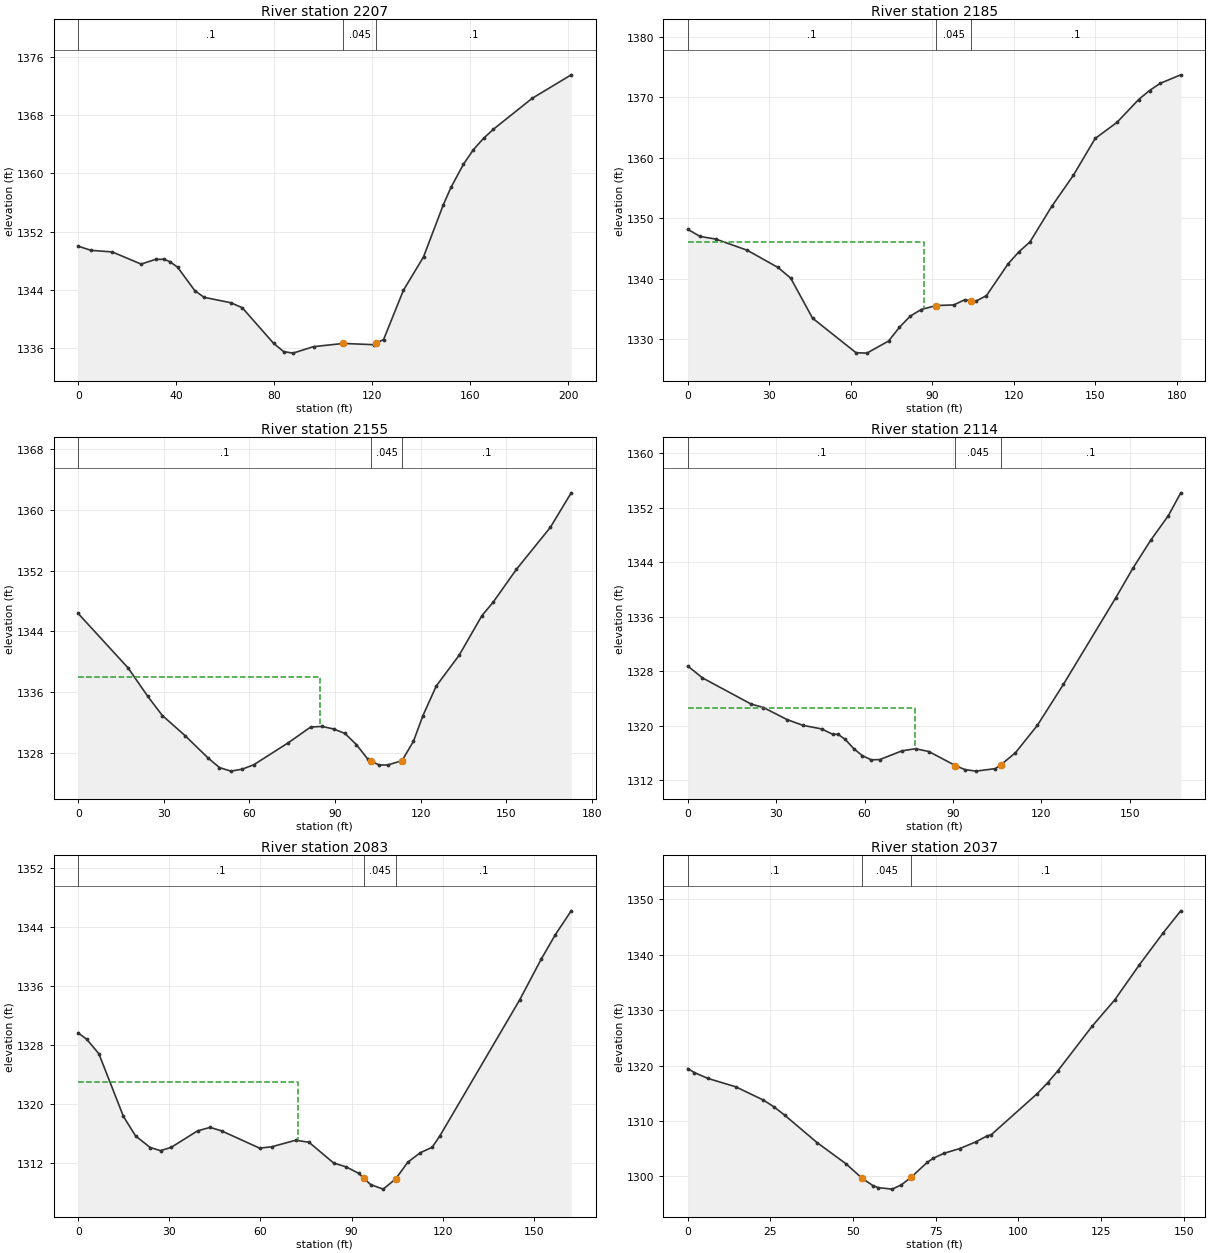
Type RM Length L Ch R = 1 ,2207    ,34.6,22,22.2
XS GIS Cut Line= 3
2147054.80492229 643775.263526062147100.06158205643824.634427612
2147073.54757936643956.290165085
#Sta/Elev= 30
       0    1350     5.2 1349.43    13.9 1349.21    25.7 1347.54    31.6 1348.19
    35.2  1348.2    37.5 1347.86    40.6 1347.11    47.6  1343.9    51.4 1342.98
    62.3 1342.24      67 1341.55    79.8 1336.66    83.9 1335.53    87.7 1335.32
    96.1 1336.21   108.3 1336.65   120.6 1336.48   121.7 1336.68   124.7 1337.19
   132.8 1343.95     141 1348.53   149.1  1355.7   152.2 1358.06   157.3 1361.25
   161.4 1363.26   165.5  1364.8   169.5 1366.04   185.3 1370.28   201.3 1373.52
#Mann= 3 ,-1,0
       0      .1       0   108.3    .045       0   121.7      .1       0
Bank Sta=108.3,121.7
XS Rating Curve= 0 ,0
Exp/Cntr(USF)=0,0
Exp/Cntr=0.3,0.1

Type RM Length L Ch R = 1 ,2185    ,29.3,29.8,40.5
XS GIS Cut Line= 3
2147050.19152873643776.9663690242147070.14139411643809.193074636
2147069.94956848 643952.67864486
#Sta/Elev= 30
       0 1348.19     4.5    1347    10.3 1346.57    21.9 1344.72    33.2 1341.88
    37.9 1340.11    45.9 1333.52    61.9 1327.81    65.9 1327.74    73.9 1329.74
    77.9 1332.02    81.9 1333.86    85.9 1334.94    91.41335.594    97.9  1335.7
   101.9 1336.55   104.41336.377   105.9 1336.29   109.9 1337.23   117.9  1342.5
   121.9 1344.49   125.9 1346.09   133.9 1351.95   141.9 1357.11   149.9 1363.17
   157.9 1365.82   165.9  1369.6   169.9 1371.09   173.9 1372.29   181.4 1373.68
#Mann= 3 ,-1,0
       0      .1       0    91.4    .045       0   104.4      .1       0
#XS Ineff= 2 , 0
            87.1 1346.14
Permanent Ineff=
       F       F
Bank Sta=91.4,104.4
XS Rating Curve= 0 ,0
Exp/Cntr(USF)=0,0
Exp/Cntr=0.3,0.1

Type RM Length L Ch R = 1 ,2155    ,63.3,40.9,54.6
XS GIS Cut Line= 2
2147040.63364499643775.7206640372147044.74788679 643948.51881947
#Sta/Elev= 30
       0 1346.37    17.5  1339.2    24.4 1335.46    29.5 1332.94    37.5 1330.28
    45.5 1327.36    49.5 1326.09    53.5 1325.62    57.5 1325.88    61.5 1326.45
    73.5 1329.32    81.5 1331.43    85.5  1331.5    89.5 1331.17    93.5 1330.58
    97.5 1329.12   101.5 1327.21   102.6 1326.94   105.5 1326.42   108.5 1326.43
   113.5    1327   117.5 1329.54   120.8  1332.9   125.5 1336.82   133.5 1340.86
   141.5 1346.08   145.4 1347.83   153.6 1352.18   165.5 1357.71   172.8 1362.25
#Mann= 3 ,-1,0
       0      .1       0   102.6    .045       0   113.5      .1       0
#XS Ineff= 2 , 0
           84.68 1337.97
Permanent Ineff=
       F       F
Bank Sta=102.6,113.5
XS Rating Curve= 0 ,0
Exp/Cntr(USF)=0,0
Exp/Cntr=0.3,0.1

Type RM Length L Ch R = 1 ,2114    ,16,31.3,21.6
XS GIS Cut Line= 3
2146989.88474672643792.2812644012146979.35445781643840.336398653
2147034.23371331643944.861715651
#Sta/Elev= 30
       0 1328.79       5 1327.05    21.4 1323.23    25.7 1322.69    33.7 1320.93
    39.1 1320.08    45.4 1319.56    49.2 1318.77      51 1318.77    53.4 1318.03
    56.4 1316.64    59.2 1315.64    62.3 1315.02    65.2 1315.06    72.7 1316.34
    77.3 1316.65    81.8 1316.24    90.8 1314.18      94 1313.59    97.8 1313.36
   104.4 1313.73   106.2 1314.27   111.2 1316.06   118.6 1320.06   127.5 1326.12
   145.2 1338.78   151.1 1343.18   157.1 1347.26   163.1 1350.88   167.3 1354.22
#Mann= 3 ,-1,0
       0      .1       0    90.8    .045       0   106.2      .1       0
#XS Ineff= 2 , 0
           77.07 1322.61
Permanent Ineff=
       F       F
Bank Sta=90.8,106.2
XS Rating Curve= 0 ,0
Exp/Cntr(USF)=0,0
Exp/Cntr=0.3,0.1

Type RM Length L Ch R = 1 ,2083    ,78.1,45.4,63.8
XS GIS Cut Line= 4
 2146965.8576876 643806.444509012146962.82665235 643826.51888773
2146980.97278587643920.9407420792147020.74455313643943.811636944
#Sta/Elev= 30
       0 1329.62     2.8 1328.76     6.8  1326.8    14.9 1318.29    18.9 1315.65
    23.7 1314.08    27.1 1313.66    30.6  1314.1    39.3 1316.34    43.4 1316.81
    47.2 1316.34    59.7    1314    63.7 1314.18    71.6 1315.07      76 1314.79
    84.1 1311.98    88.2 1311.46    92.3 1310.5993.963881309.935    96.3 1309.05
   100.4 1308.44   104.5 1309.82   108.5 1312.09   112.6 1313.37   116.5 1314.11
     119 1315.61   145.3 1334.07   152.4  1339.6   157.1 1342.95   162.3 1346.17
#Mann= 3 ,-1,0
       0      .1       093.96388    .045       0   104.5      .1       0
#XS Ineff= 2 , 0
           72.51 1323.03
Permanent Ineff=
       F       F
Bank Sta=93.96388,104.5
XS Rating Curve= 0 ,0
Exp/Cntr(USF)=0,0
Exp/Cntr=0.3,0.1

Type RM Length L Ch R = 1 ,2037    ,70.4,69.4,66.7
XS GIS Cut Line= 4
 2146905.2802734643867.3190413572146917.12399843643904.542177149
2146959.84600655 643935.420460252147013.14276917643956.569969224
#Sta/Elev= 30
       0 1319.47       2 1318.75     6.1 1317.69    14.5 1316.18    22.9 1313.78
    26.1 1312.55    29.3 1311.07    39.1 1306.11    47.8 1302.31    52.7 1299.68
      56 1298.35    57.6 1297.98    61.8 1297.71    64.6 1298.48    67.5 1299.82
    72.4 1302.53    74.3  1303.3    77.4 1304.16    82.3 1305.04    87.2 1306.26
    90.4 1307.28    91.8 1307.54   105.7 1314.95   108.8 1316.88   111.9 1319.05
   122.3 1327.12   129.1 1331.84   136.5 1338.13   143.8 1343.98   149.1 1347.94
#Mann= 3 ,-1,0
       0      .1       0    52.7    .045       0    67.5      .1       0
Bank Sta=52.7,67.5
XS Rating Curve= 0 ,0
Exp/Cntr(USF)=0,0
Exp/Cntr=0.3,0.1

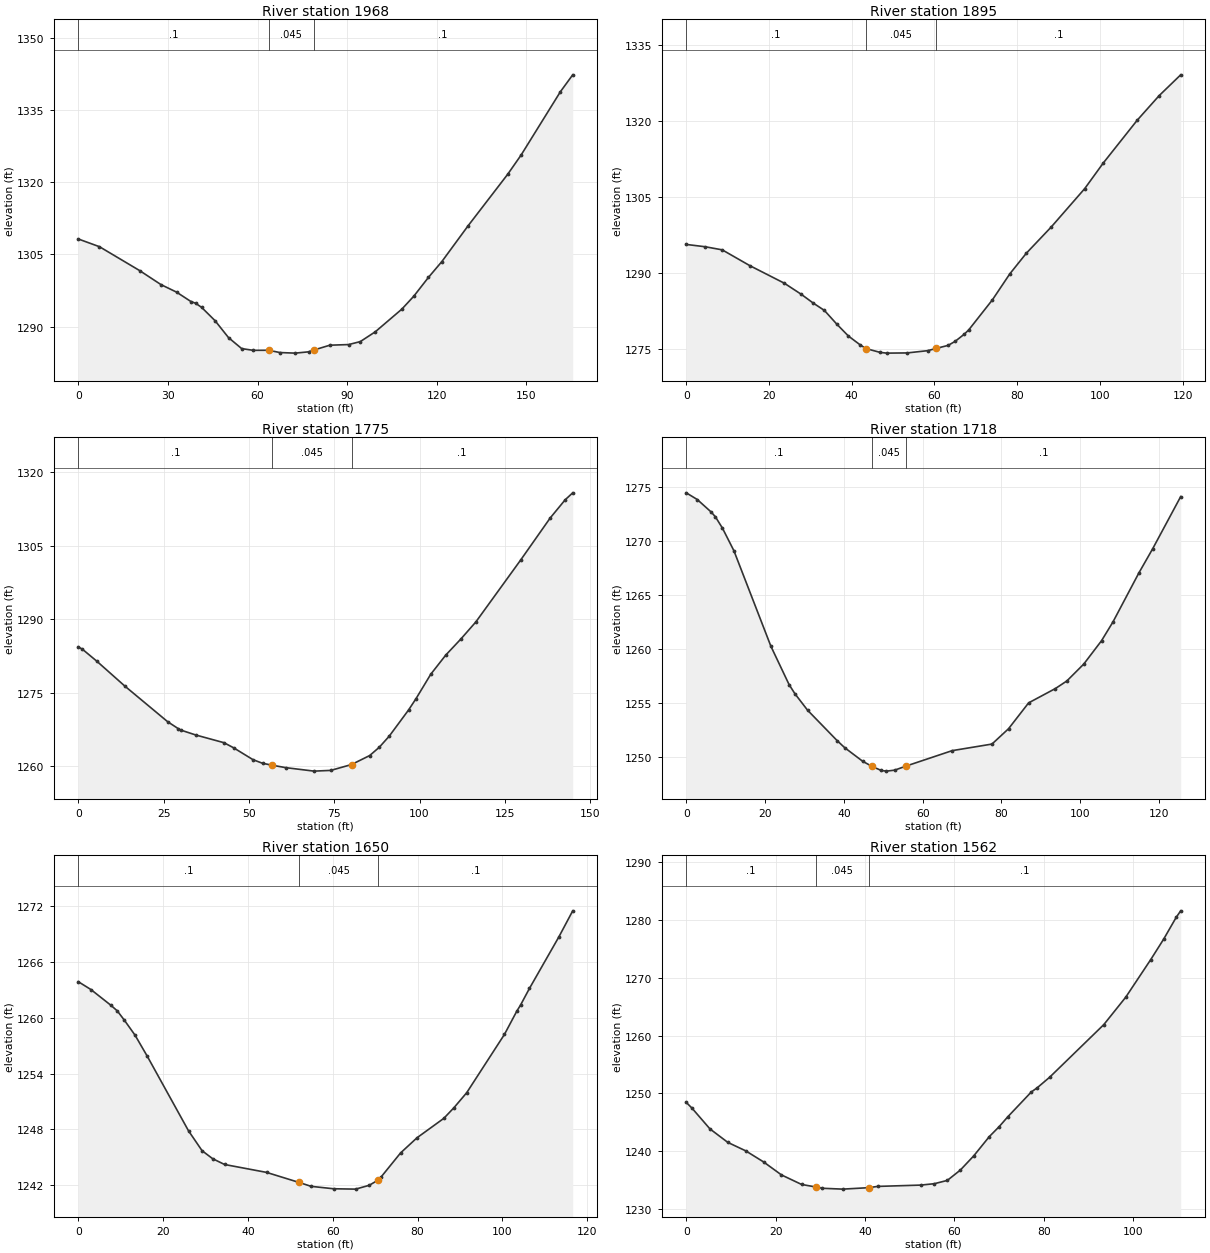
Type RM Length L Ch R = 1 ,1968    ,66.3,72.5,72
XS GIS Cut Line= 4
2146840.73856598643923.7009951222146863.76803131 643951.90034042
2146934.73638364643987.1495220422146979.85533612644008.299031015
#Sta/Elev= 30
       0 1308.22     7.1 1306.61    20.5 1301.66    27.7 1298.72    32.9 1297.16
    37.7 1295.21    39.3 1294.84    41.3 1293.98    45.8 1291.21    50.3 1287.69
    54.7 1285.41    58.6 1285.05    63.7 1285.07    67.5 1284.59    72.6 1284.47
    77.1 1284.74    78.8  1285.1    84.2 1286.12    90.5 1286.25    94.4 1286.87
    99.4  1288.9   108.3 1293.62   112.3 1296.31   117.2 1300.22   121.7 1303.52
   130.5 1310.98   143.7 1321.65   148.2 1325.66   161.4 1338.88   165.5 1342.37
#Mann= 3 ,-1,0
       0      .1       0    63.7    .045       0    78.8      .1       0
Bank Sta=63.7,78.8
XS Rating Curve= 0 ,0
Exp/Cntr(USF)=0,0
Exp/Cntr=0.3,0.1

Type RM Length L Ch R = 1 ,1895    ,114.4,120,122.9
XS GIS Cut Line= 4
2146837.44864236  643984.7995766 2146844.0284896644007.359052838
2146889.61743117644040.7282781072146924.86661279644058.587863462
#Sta/Elev= 30
       0 1295.59     4.6 1295.13     8.7 1294.52    15.4 1291.39    23.7 1287.94
    27.8 1285.75    30.6 1284.07    33.4 1282.56    36.4 1279.85    39.2 1277.51
    42.1 1275.73    43.5 1275.02    46.9 1274.28    48.5 1274.14    53.4 1274.18
    58.4 1274.63    60.4 1275.07    63.3 1275.67      65 1276.47    67.2 1277.88
    68.3 1278.75      74 1284.66    78.2 1289.78    82.2 1293.86    88.2 1299.02
    96.3  1306.6   100.8 1311.67     109 1320.11   114.3 1324.96   119.5 1329.06
#Mann= 3 ,-1,0
       0      .1       0    43.5    .045       0    60.4      .1       0
Bank Sta=43.5,60.4
XS Rating Curve= 0 ,0
Exp/Cntr(USF)=0,0
Exp/Cntr=0.3,0.1

Type RM Length L Ch R = 1 ,1775    ,54.9,57.7,61.3
XS GIS Cut Line= 4
2146752.00045731644040.0056087852146763.04050099644078.074724937
2146799.20616134644123.7576643192146842.22426259644142.792222395
#Sta/Elev= 30
       0  1284.4     1.2 1283.93     5.4  1281.5    13.7 1276.37    26.2 1269.13
    29.3 1267.72    30.1 1267.41    34.5 1266.41    42.7 1264.85    45.5 1263.82
    51.2 1261.39      54 1260.65    56.9 1260.25    60.8 1259.76    69.1 1259.05
      74  1259.2    80.1  1260.4    85.4 1262.23    88.2 1263.91    91.1 1266.16
    96.8 1271.53      99 1273.86   103.3 1278.82   107.7 1282.73   112.1 1285.99
   116.5 1289.48   129.6 1302.08   138.3  1310.7   142.7 1314.42   144.9 1315.83
#Mann= 3 ,-1,0
       0      .1       0    56.9    .045       0    80.1      .1       0
Bank Sta=56.9,80.1
XS Rating Curve= 0 ,0
Exp/Cntr(USF)=0,0
Exp/Cntr=0.3,0.1

Type RM Length L Ch R = 1 ,1718    ,69.2,67.9,67.8
XS GIS Cut Line= 2
2146701.89440379644078.8031430112146766.80799657644186.230567685
#Sta/Elev= 30
       0 1274.46     2.8 1273.84     6.3 1272.69     7.4 1272.24     9.2 1271.18
    12.1 1269.09    21.5 1260.22    26.1 1256.68    27.6 1255.82    30.8  1254.3
    38.3 1251.48    40.2 1250.83    44.8 1249.56    47.1  1249.1    49.5 1248.71
    50.8 1248.65    52.9 1248.74    55.8 1249.12    67.5 1250.55    77.6 1251.16
    81.8 1252.58    86.9 1254.98    93.7 1256.31    96.6 1257.01   100.9 1258.58
   105.4 1260.74   108.3 1262.48   114.9 1267.04   118.4 1269.28   125.5 1274.11
#Mann= 3 ,-1,0
       0      .1       0    47.1    .045       0    55.8      .1       0
Bank Sta=47.1,55.8
XS Rating Curve= 0 ,0
Exp/Cntr(USF)=0,0
Exp/Cntr=0.3,0.1

Type RM Length L Ch R = 1 ,1650    ,80.4,87.9,90.8
XS GIS Cut Line= 4
2146659.28811547 644128.364038982146664.99785192644146.587010704
2146714.37108599644188.9441376892146743.09661883644204.053381435
#Sta/Elev= 30
       0 1263.89       3 1263.04     7.7 1261.35     9.2 1260.75    10.9 1259.73
    13.4 1258.13    16.3 1255.85      26 1247.85    29.2 1245.71    31.7 1244.85
    34.5 1244.23    44.4 1243.38    52.11242.295    54.9 1241.88    60.2 1241.62
    65.4 1241.58    68.6 1241.99    70.7 1242.55    71.4 1242.88      76 1245.47
    79.9 1247.11    86.2 1249.19    88.6 1250.34    91.6 1251.95   100.5 1258.22
   103.4 1260.71   104.3 1261.38   106.4 1263.17   113.3 1268.68   116.6 1271.51
#Mann= 3 ,-1,0
       0      .1       0    52.1    .045       0    70.7      .1       0
Bank Sta=52.1,70.7
XS Rating Curve= 0 ,0
Exp/Cntr(USF)=0,0
Exp/Cntr=0.3,0.1

Type RM Length L Ch R = 1 ,1562    ,64.5,65.2,65.5
XS GIS Cut Line= 4
2146622.92290092644183.9125308062146621.78082743644205.611927012
2146643.09953248644243.3003520032146676.98104585644273.755644924
#Sta/Elev= 30
       0 1248.43     1.3 1247.42     5.3 1243.84     9.3  1241.5    13.3 1240.04
    17.3 1238.12    21.3 1235.87    25.8 1234.22      29 1233.78    30.4 1233.56
      35 1233.41    40.8 1233.66    42.8 1233.88    52.5 1234.11    55.5 1234.35
    58.4 1234.92    61.3  1236.7    64.3 1239.16    67.8 1242.51      70 1244.23
    71.9 1245.91    77.2 1250.24    78.5 1250.95    81.3 1252.79    93.4 1261.89
    98.3 1266.63   103.9 1273.15   106.8  1276.7   109.6 1280.47   110.6 1281.59
#Mann= 3 ,-1,0
       0      .1       0      29    .045       0    40.8      .1       0
Bank Sta=29,40.8
XS Rating Curve= 0 ,0
Exp/Cntr(USF)=0,0
Exp/Cntr=0.3,0.1

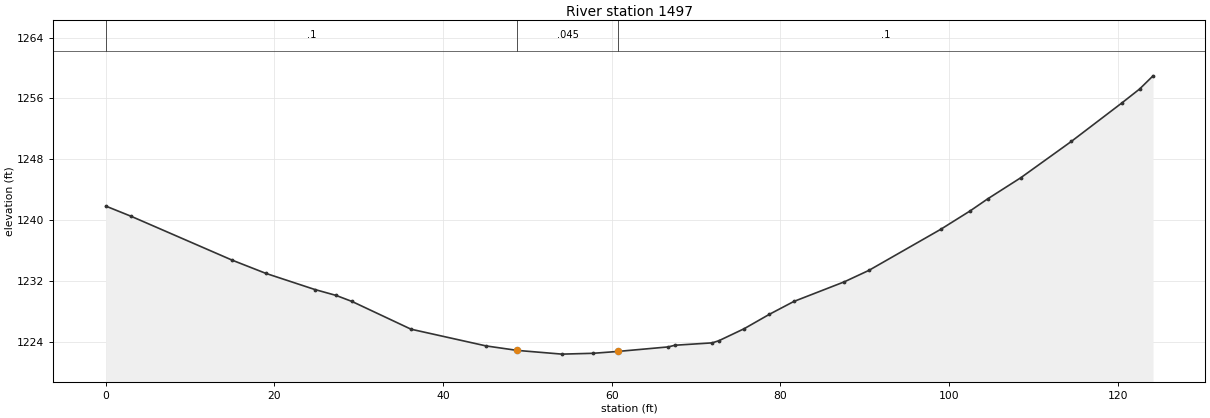
Type RM Length L Ch R = 1 ,1497    ,49,49.8,49.1
XS GIS Cut Line= 4
2146567.34199134644202.1857065592146566.19991785644226.930632057
 2146594.3710638644283.6536151232146621.40013627644307.637158299
#Sta/Elev= 30
       0 1241.83       3 1240.49      15 1234.71      19 1232.97    24.8 1230.85
    27.3 1230.08    29.2 1229.28    36.2 1225.63    45.1 1223.43    48.8 1222.84
    54.1 1222.35    57.8 1222.46    60.7  1222.7    66.7  1223.3    67.5 1223.52
    71.9 1223.83    72.7 1224.11    75.7 1225.69    78.7 1227.59    81.6 1229.28
    87.6 1231.87    90.5 1233.37      99 1238.76   102.5 1241.19   104.6 1242.79
   108.5 1245.55   114.5 1250.33   120.5  1255.4   122.6 1257.23   124.2 1258.97
#Mann= 3 ,-1,0
       0      .1       0    48.8    .045       0    60.7      .1       0
Bank Sta=48.8,60.7
XS Rating Curve= 0 ,0
Exp/Cntr(USF)=0,0
Exp/Cntr=0.3,0.1