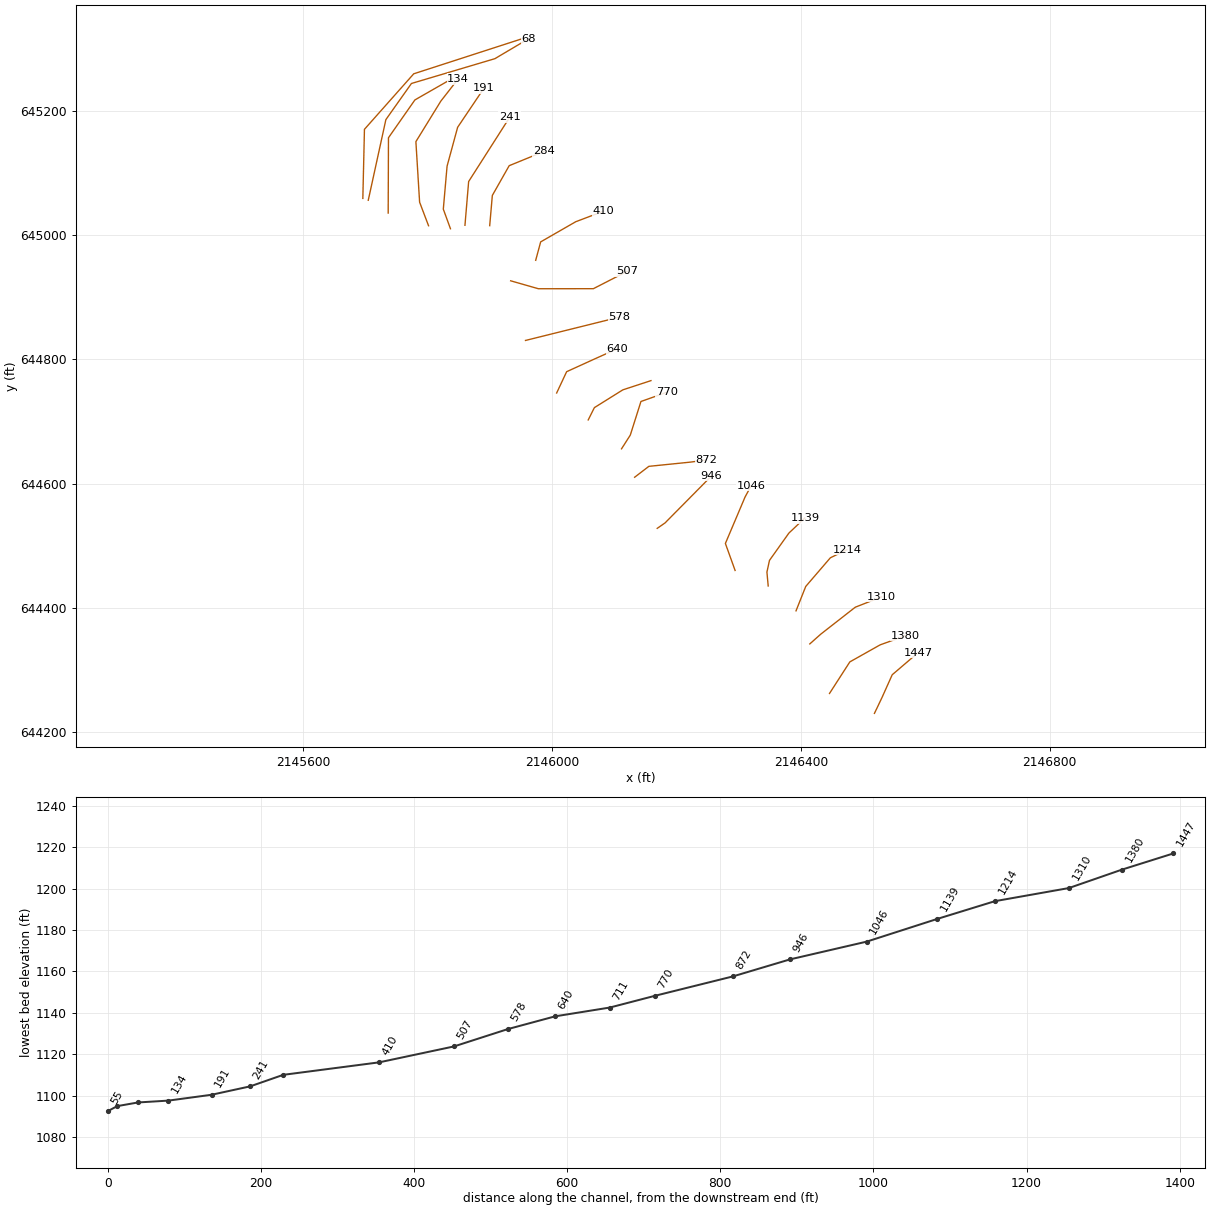
HEC-RAS study CAVERN.prj: CAVERN

--- CAVERN.g01 (geometry) --- (continued)

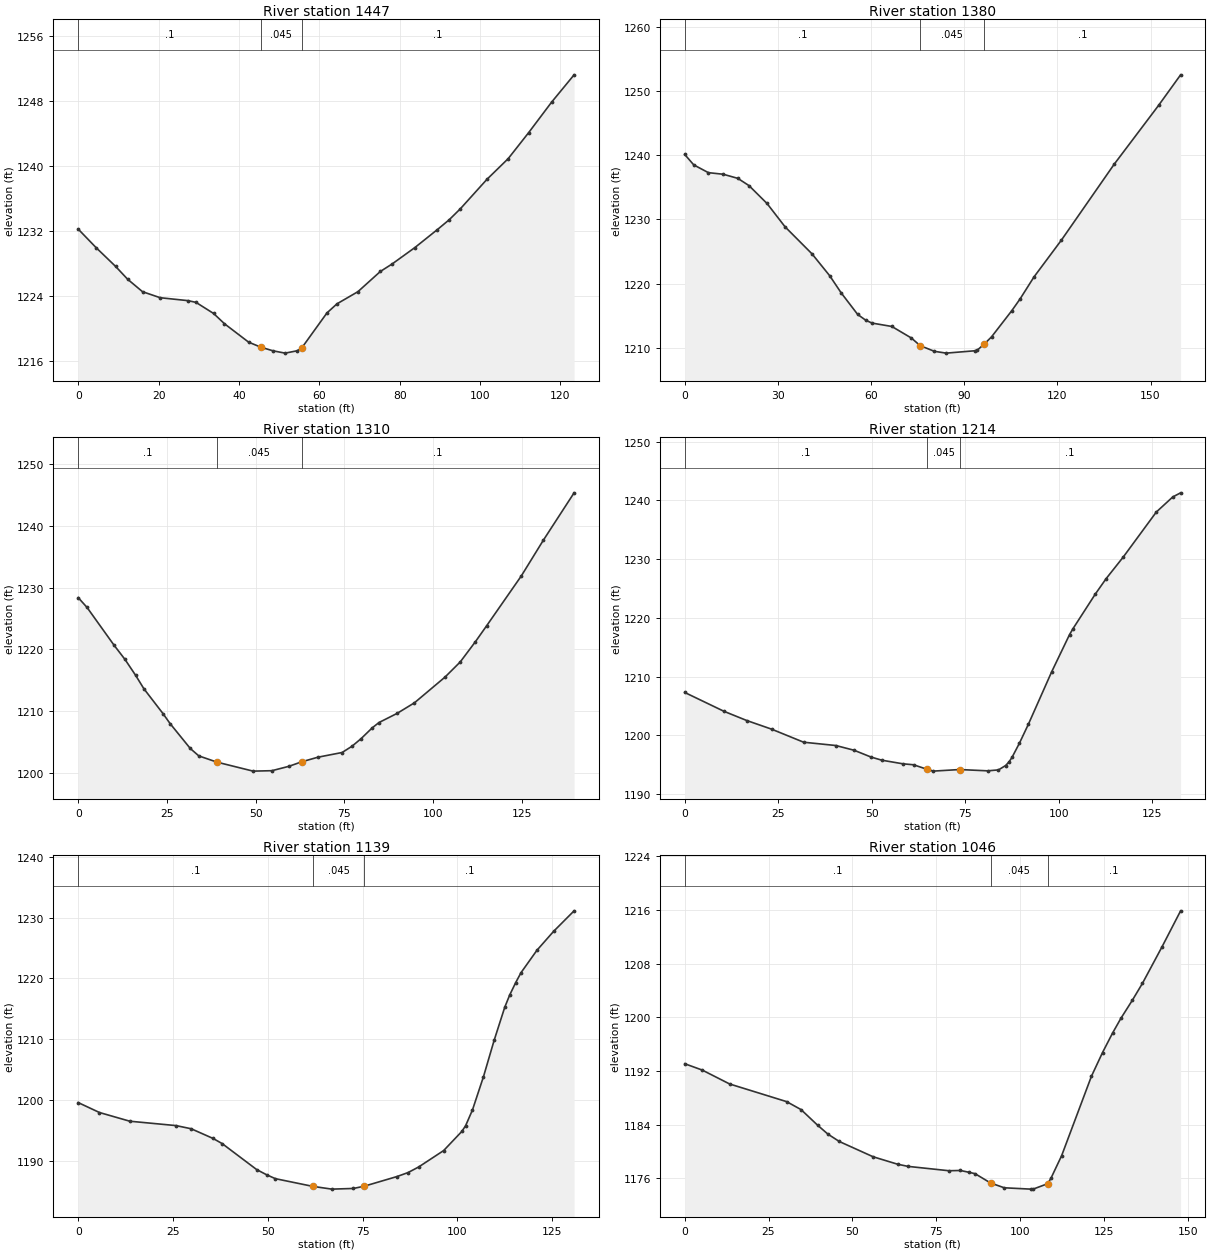
Type RM Length L Ch R = 1 ,1447    ,72.3,67.2,57.9
XS GIS Cut Line= 4
 2146518.2328315644230.7375436722146530.41494867644256.243851494
2146546.78466862   644292.7902032146588.66069638644328.575172183
#Sta/Elev= 30
       0 1232.26     4.5 1229.96     9.3 1227.68    12.3  1226.1      16 1224.57
    20.4 1223.83    27.3 1223.47    29.3 1223.26    33.7 1221.89    36.4 1220.63
    42.4 1218.37    45.4 1217.76    48.5  1217.3    51.5 1217.02    54.5 1217.31
    55.6 1217.64    61.9 1221.96    64.4 1223.08    69.6 1224.57    75.2 1227.06
    78.1 1227.97    83.8    1230    89.4 1232.21    92.3  1233.4    95.1 1234.76
   101.7 1238.37     107 1240.92   112.1 1244.12   117.8 1247.86   123.4 1251.22
#Mann= 3 ,-1,0
       0      .1       0    45.4    .045       0    55.6      .1       0
Bank Sta=45.4,55.6
XS Rating Curve= 0 ,0
Exp/Cntr(USF)=0,0
Exp/Cntr=0.3,0.1

Type RM Length L Ch R = 1 ,1380    ,67.4,69.4,71.3
XS GIS Cut Line= 4
2146445.99825491644262.7683128722146478.66701255644313.494592672
2146527.39548122644340.9043563012146568.33525812644355.610291952
#Sta/Elev= 30
       0 1240.12     2.9  1238.5     7.6 1237.29    12.4 1237.04    17.1  1236.4
    20.7 1235.27    26.5 1232.49    32.3 1228.86      41 1224.64    46.7 1221.23
    50.4 1218.56    55.7 1215.21    58.3 1214.31    60.3 1213.87    66.7 1213.34
      73 1211.54    75.8 1210.36    80.4 1209.47    84.2 1209.19    93.5 1209.56
    94.2 1209.65    96.5 1210.62    98.8 1211.72   105.3 1215.78     108 1217.63
   112.5 1221.07   121.3 1226.78   138.3  1238.6   152.6 1247.76   159.7 1252.52
#Mann= 3 ,-1,0
       0      .1       0    75.8    .045       0    96.5      .1       0
Bank Sta=75.8,96.5
XS Rating Curve= 0 ,0
Exp/Cntr(USF)=0,0
Exp/Cntr=0.3,0.1

Type RM Length L Ch R = 1 ,1310    ,93.9,96.6,92.2
XS GIS Cut Line= 4
2146414.33020625644342.4271209472146431.84199968 644358.03545857
2146487.42290926644401.4342509822146530.06031935644418.184662089
#Sta/Elev= 30
       0  1228.4     2.5  1226.8    10.1 1220.69    13.2 1218.37    16.2 1215.79
    18.5 1213.64    23.9  1209.6    25.9 1207.98    31.6 1203.94      34 1202.74
    39.1 1201.73    49.3 1200.27    54.6 1200.34    59.4 1201.05      63 1201.78
    67.6 1202.53    74.4 1203.29    77.2 1204.31    79.7 1205.51    82.9 1207.29
    84.8 1208.15    89.9 1209.63    94.8 1211.35   103.4 1215.51   107.7 1217.97
     112 1221.27   115.2 1223.88   124.9  1231.9   131.1 1237.68   139.8 1245.39
#Mann= 3 ,-1,0
       0      .1       0    39.1    .045       0      63      .1       0
Bank Sta=39.1,63
XS Rating Curve= 0 ,0
Exp/Cntr(USF)=0,0
Exp/Cntr=0.3,0.1

Type RM Length L Ch R = 1 ,1214    ,73.8,75.1,75.5
XS GIS Cut Line= 4
2146392.16189117644395.6094099482146407.77022879644434.820599584
2146447.36210959644480.8842301272146474.01049089644493.827729619
#Sta/Elev= 30
       0 1207.32    10.5 1204.11    16.6 1202.54    23.2 1201.08    31.8 1198.85
    40.4 1198.29    45.3 1197.48    49.8 1196.33    52.7 1195.79    58.3 1195.18
    61.2 1195.01    64.91194.218    66.4 1193.93    73.5  1194.2      81 1193.98
    83.9 1194.14    85.8 1194.88    86.7 1195.49    87.5 1196.25    89.5 1198.69
    91.9 1201.92    98.1 1210.81   102.9 1217.17   103.8 1218.16   109.8 1224.08
   112.7 1226.71   117.2 1230.32   126.1 1238.03   130.5  1240.6   132.6  1241.3
#Mann= 3 ,-1,0
       0      .1       0    64.9    .045       0    73.5      .1       0
Bank Sta=64.9,73.5
XS Rating Curve= 0 ,0
Exp/Cntr(USF)=0,0
Exp/Cntr=0.3,0.1

Type RM Length L Ch R = 1 ,1139    ,85.6,92.3,91.5
XS GIS Cut Line= 5
2146347.41960884644435.5963426852146345.36387656644457.866775633
2146349.47534111644476.7109881282146380.65394724644520.566609935
2146406.35060064644544.892775155
#Sta/Elev= 30
       0 1199.59     5.6 1197.96    13.6 1196.53    25.8 1195.81    29.8 1195.29
    35.6 1193.69      38 1192.84    47.1 1188.57    49.7 1187.73      52 1187.09
    61.9 1185.82    66.9 1185.37    72.6 1185.48    75.5 1185.86    84.1 1187.44
      87 1188.09    89.8 1189.01    96.4 1191.71   101.2 1194.86   102.2 1195.81
     104 1198.39   106.9 1203.85   109.7  1209.8   112.5 1215.24   113.8 1217.25
   115.4 1219.31   116.8 1220.94     121 1224.62   125.4 1227.73   130.8  1231.1
#Mann= 3 ,-1,0
       0      .1       0    61.9    .045       0    75.5      .1       0
Bank Sta=61.9,75.5
XS Rating Curve= 0 ,0
Exp/Cntr(USF)=0,0
Exp/Cntr=0.3,0.1

Type RM Length L Ch R = 1 ,1046    ,100.3,100.2,91.5
XS GIS Cut Line= 4
2146294.19363922 644460.536237582146278.58530159644503.935029992
  2146310.182668644578.550497649 2146320.0806382644596.823673401
#Sta/Elev= 30
       0 1193.07     5.2 1192.13    13.4 1190.05    30.4 1187.42    34.7 1186.23
    39.6 1183.92    42.7 1182.58    46.1 1181.48    56.2  1179.2    63.5 1178.09
    66.6 1177.77    78.8 1177.12    82.2 1177.16    84.9 1176.88    86.6 1176.68
    91.2  1175.3    95.3 1174.58   103.2 1174.38   103.9 1174.38   108.3  1175.2
   109.3 1176.08   112.4 1179.35   121.3  1191.2   124.6 1194.73   127.6 1197.64
   130.1 1199.85   133.5 1202.53   136.5 1205.04   142.4 1210.54   147.9 1215.86
#Mann= 3 ,-1,0
       0      .1       0    91.2    .045       0   108.3      .1       0
Bank Sta=91.2,108.3
XS Rating Curve= 0 ,0
Exp/Cntr(USF)=0,0
Exp/Cntr=0.3,0.1

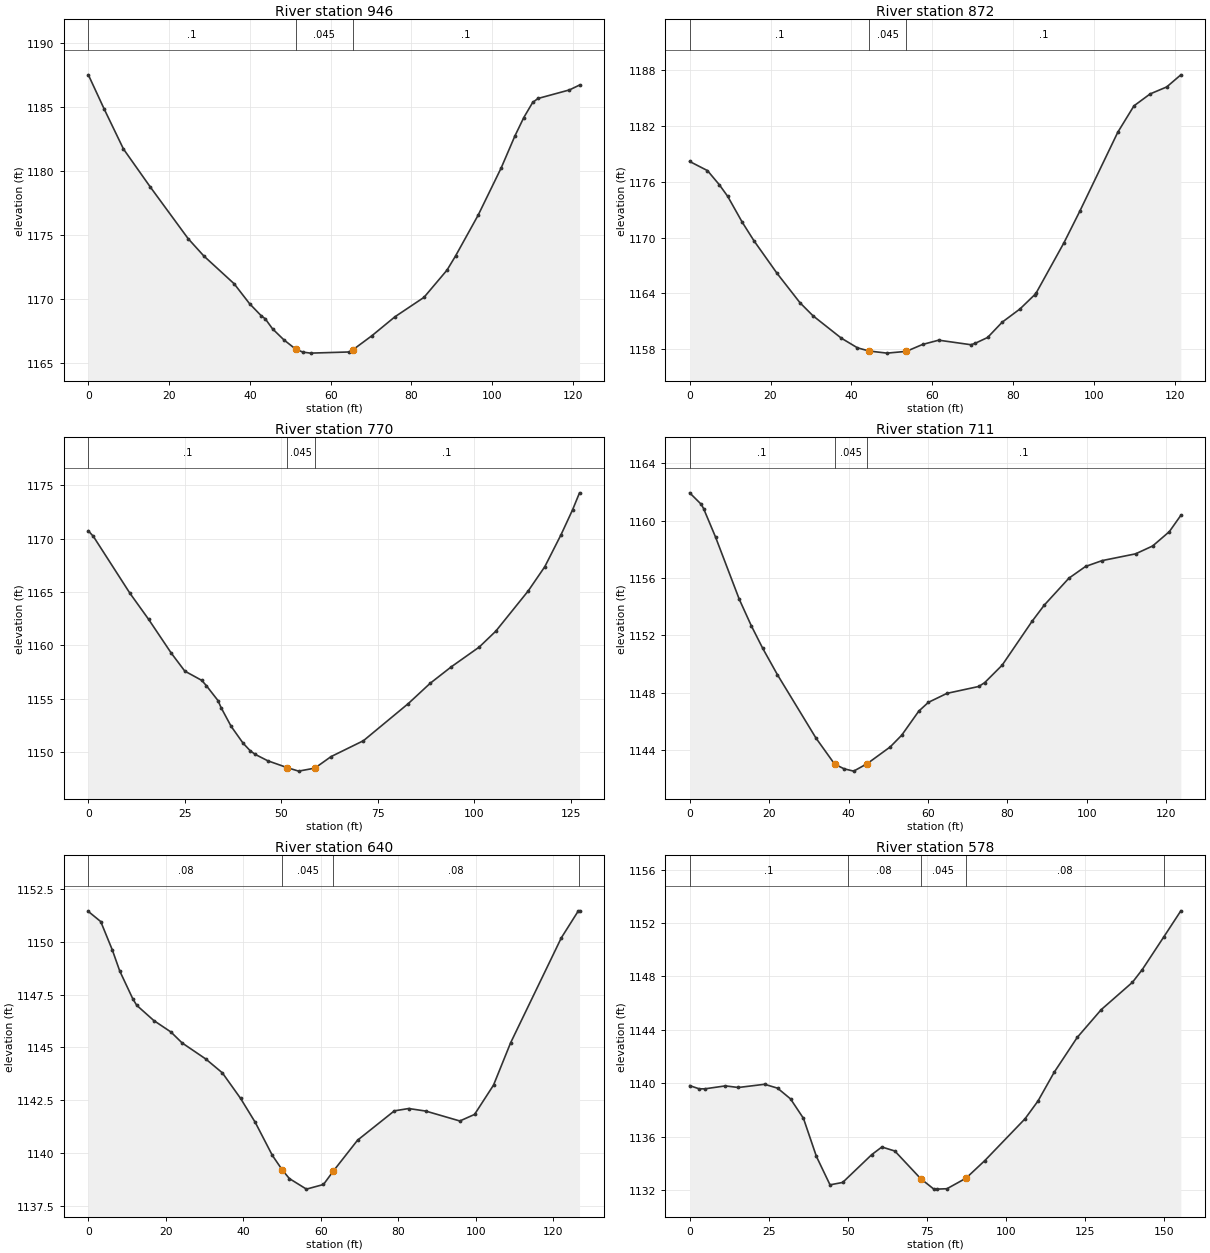
Type RM Length L Ch R = 1 ,946     ,81.4,74.3,66.7
XS GIS Cut Line= 3
2146168.98960733644528.2243230442146181.59389751644536.978451468
2146256.29318577644612.516467783
#Sta/Elev= 30
       0 1187.54     3.9 1184.88     8.7 1181.74    15.3 1178.79    24.7 1174.74
    28.6 1173.38    36.1 1171.21    39.9 1169.66    42.8 1168.71    43.8 1168.47
    45.6 1167.69    48.4 1166.83    51.3 1166.11    53.1 1165.87      55 1165.79
    64.5 1165.88    65.4 1166.03    70.2 1167.15    75.9 1168.63    83.1 1170.15
    88.8 1172.28    90.9 1173.38    96.5 1176.57   102.2 1180.26   105.6 1182.76
   107.8  1184.2     110 1185.38   111.3 1185.69   119.1 1186.36   121.6 1186.74
#Mann= 3 ,-1,0
       0      .1       0    51.3    .045       0    65.4      .1       0
Bank Sta=51.3,65.4
XS Rating Curve= 0 ,0
Exp/Cntr(USF)=0,0
Exp/Cntr=0.3,0.1

Type RM Length L Ch R = 1 ,872     ,89.7,101.9,110.9
XS GIS Cut Line= 4
2146132.67906845644610.4066977622146155.52053814644627.918491191
2146222.90287372644634.7709320992146247.64779922644638.197152552
#Sta/Elev= 30
       0 1178.16     4.4 1177.18     7.3 1175.68     9.4 1174.42      13 1171.64
    15.9 1169.65    21.6 1166.16    27.3 1162.99    30.5  1161.6    37.5  1159.2
    41.5 1158.16    44.41157.814    48.8 1157.59    53.6 1157.78    57.6 1158.52
    61.6 1158.98    69.6 1158.49    70.7 1158.66    73.7 1159.27    77.3 1160.91
    81.7 1162.33    85.3 1163.84    85.7 1164.04    92.6 1169.45    96.5 1172.82
   105.9  1181.3   109.9 1184.13   113.9 1185.41     118 1186.16   121.5 1187.46
#Mann= 3 ,-1,0
       0      .1       0    44.4    .045       0    53.6      .1       0
Bank Sta=44.4,53.6
XS Rating Curve= 0 ,0
Exp/Cntr(USF)=0,0
Exp/Cntr=0.3,0.1

Type RM Length L Ch R = 1 ,770     ,65.8,59.1,53.2
XS GIS Cut Line= 4
2146111.59849121644656.0677043192146125.68406418644678.147791687
2146142.81516645644732.2059366222146184.69119422644747.052891921
#Sta/Elev= 30
       0 1170.72     1.3  1170.2    10.8 1164.86    15.6 1162.44    21.5 1159.26
      25 1157.58    29.4 1156.71    30.6 1156.21    33.6 1154.82    34.4 1154.16
      37 1152.41    40.1 1150.83      42  1150.1    43.3 1149.77    46.5 1149.18
    51.6 1148.53    54.5 1148.21    58.7 1148.49    62.9 1149.57    71.3 1151.06
    82.9 1154.53    88.6 1156.44    94.1 1157.99   101.3 1159.83   105.6 1161.32
     114 1165.09   118.3 1167.36   122.5 1170.35   125.5 1172.69   127.3 1174.28
#Mann= 3 ,-1,0
       0      .1       0    51.6    .045       0    58.7      .1       0
Bank Sta=51.6,58.7
XS Rating Curve= 0 ,0
Exp/Cntr(USF)=0,0
Exp/Cntr=0.3,0.1

Type RM Length L Ch R = 1 ,711     ,72.8,71.3,69.4
XS GIS Cut Line= 4
2146058.05872683644702.5426623492146067.95669703644722.338602748
2146113.63963641644750.8904398622146158.94188463 644765.73739516
#Sta/Elev= 30
       0 1161.95     2.9 1161.15     3.5 1160.85     6.5 1158.87    12.5 1154.51
    15.5 1152.68    18.4 1151.09    22.1 1149.25    31.8 1144.83    36.5 1143.01
    38.9 1142.68    41.3 1142.52    44.7 1143.04    50.5 1144.21    53.4 1145.03
    57.7 1146.71    60.1 1147.32    64.8 1147.95    72.8 1148.43    74.3  1148.7
    78.7 1149.92    86.2 1152.97    89.3 1154.11    95.5 1155.99    99.7 1156.81
   103.9 1157.22   112.3 1157.69   116.6 1158.24   120.8 1159.24   123.7 1160.38
#Mann= 3 ,-1,0
       0      .1       0    36.5    .045       0    44.7      .1       0
Bank Sta=36.5,44.7
XS Rating Curve= 0 ,0
Exp/Cntr(USF)=0,0
Exp/Cntr=0.3,0.1

Type RM Length L Ch R = 1 ,640     ,64,61.9,59.9
XS GIS Cut Line= 5
2146007.28661795644745.8520407882146023.36024477644780.114245324
2146070.73514487644801.6867444772146098.13262463644813.948940569
2146104.48130139 644816.49563066
#Sta/Elev= 30
       0 1151.44     3.2 1150.96     6.2 1149.61     8.1 1148.62    11.5 1147.29
    12.5 1146.99    16.9 1146.27    21.3 1145.73    24.2 1145.21    30.3 1144.45
    34.6 1143.79    39.3 1142.58    43.1 1141.44    47.5 1139.88    50.1 1139.18
    51.9 1138.78    56.3 1138.28    60.7  1138.5    63.21139.125    69.5  1140.6
      79 1141.99    82.7  1142.1    87.1 1141.98    95.9 1141.51    99.7 1141.82
   104.6 1143.21     109 1145.21   122.1 1150.19   126.4 1151.44   126.8 1151.47
#Mann= 4 ,-1,0
       0     .08       0    50.1    .045       0    63.2     .08       0
  126.76      .1       0
Bank Sta=50.1,63.2
XS Rating Curve= 0 ,0
Exp/Cntr(USF)=0,0
Exp/Cntr=0.3,0.1

Type RM Length L Ch R = 1 ,578     ,72.5,70.1,66.8
XS GIS Cut Line= 2
2145957.21663871644830.3379777522146108.07217123644867.823291893
#Sta/Elev= 30
       0 1139.84       3  1139.6     4.8  1139.6    11.3 1139.82    15.4  1139.7
    23.7 1139.94    27.8 1139.65    31.9 1138.85      36 1137.39    40.1 1134.54
    44.4 1132.42    48.4  1132.6    57.6 1134.68    60.8 1135.25    64.9 1134.95
    73.1 1132.88    77.2 1132.11    78.1  1132.1    81.4 1132.13   87.44 1132.92
    93.4 1134.24   106.1 1137.36   110.2 1138.69   115.3 1140.83   122.6 1143.44
   130.2 1145.52   140.1 1147.57   143.2 1148.52     150 1150.96   155.4 1152.91
#Mann= 5 ,-1,0
       0      .1       0      50     .08       0    73.1    .045       0
   87.44     .08       0     150      .1       0
Bank Sta=73.1,87.44
XS Rating Curve= 0 ,0
Exp/Cntr(USF)=0,0
Exp/Cntr=0.3,0.1

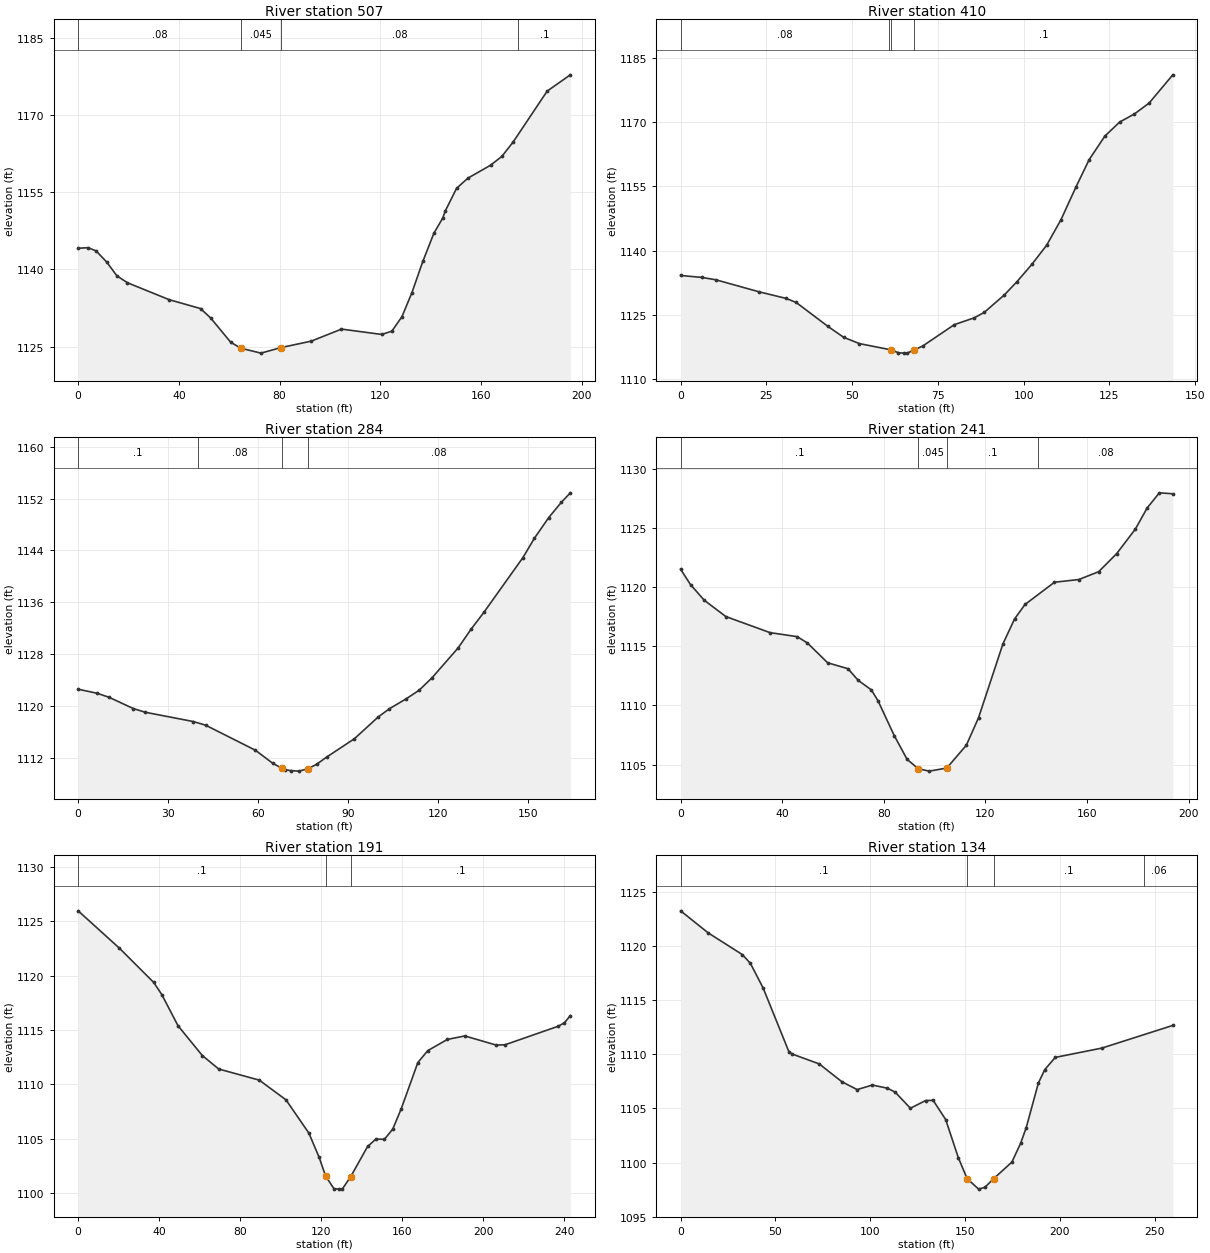
Type RM Length L Ch R = 1 ,507     ,91.8,97.8,102.4
XS GIS Cut Line= 4
2145933.33974376644926.2509859922145977.92745263644913.485129348
2146066.34665575644913.561280603 2146120.3954009644941.290636813
#Sta/Elev= 30
       0 1144.12     3.9 1144.23     7.1 1143.62    11.3 1141.46    15.4 1138.76
    19.6 1137.41    36.2 1134.12    48.6  1132.4    52.6 1130.59    60.6 1125.85
    64.6  1124.7    72.6 1123.74    80.6 1124.82    92.6 1126.07   104.6 1128.41
   120.6 1127.37   124.6 1128.01   128.6 1130.81   132.6 1135.52   136.9 1141.56
   141.3 1147.03   144.8 1149.98   145.8 1151.34   150.3 1155.76   154.8 1157.74
   163.8 1160.25   168.3 1161.97   172.8 1164.78   186.3 1174.66   195.5 1177.82
#Mann= 4 ,-1,0
       0     .08       0    64.6    .045       0    80.6     .08       0
   174.8      .1       0
Bank Sta=64.6,80.6
XS Rating Curve= 0 ,0
Exp/Cntr(USF)=0,0
Exp/Cntr=0.3,0.1

Type RM Length L Ch R = 1 ,410     ,118.7,125.3,129.7
XS GIS Cut Line= 4
2145973.59053766644959.1908385092145981.58035216644988.800151071
2146037.97904275645021.2293981622146082.62800614645038.149005341
#Sta/Elev= 30
       0 1134.17     6.2 1133.72    10.3 1133.16    22.8 1130.37    30.7 1128.83
    33.7 1127.87    42.9 1122.31    47.5 1119.75    52.1 1118.27    61.3 1116.81
    63.5 1116.13    65.1 1116.04      66 1116.04      68 1116.72    70.6 1117.71
    79.8 1122.69    85.6 1124.28    88.5 1125.54    94.4 1129.64    98.1 1132.76
   102.4 1136.76   106.7 1141.21   110.9  1147.2   115.2 1154.72   119.1 1161.21
   123.7 1166.72     128 1169.99   132.3 1171.88   136.6 1174.43   143.5 1181.02
#Mann= 4 ,-1,0
       0     .08       0   60.67      .1       0    61.3    .045       0
      68      .1       0
Bank Sta=61.3,68
XS Rating Curve= 0 ,0
Exp/Cntr(USF)=0,0
Exp/Cntr=0.3,0.1

Type RM Length L Ch R = 1 ,284     ,43.6,43.1,42.7
XS GIS Cut Line= 4
2145899.65536577645014.8806629212145903.88526757645063.524533558
2145930.95663905645111.3224238372145986.79134274645134.163893528
#Sta/Elev= 30
       0 1122.62     6.3    1122    10.3 1121.38    18.4 1119.64    22.4 1119.07
    38.4 1117.64    42.5 1117.08    59.1 1113.22    64.9  1111.2    67.9 1110.46
    69.1 1110.22    70.8 1110.08    73.7    1110    76.7 1110.38    79.6 1111.08
    82.9 1112.18    92.1 1114.99   100.1 1118.37   103.8 1119.62   109.4 1121.15
   113.7 1122.47     118 1124.39   126.7 1128.99     131 1131.87   135.3 1134.48
   148.3 1142.91   152.1 1145.87   156.9 1149.07   161.1 1151.42   164.1 1152.88
#Mann= 4 ,-1,0
       0      .1       0      40     .08       0    67.9    .045       0
    76.7     .08       0
Bank Sta=67.9,76.7
XS Rating Curve= 0 ,0
Exp/Cntr(USF)=0,0
Exp/Cntr=0.3,0.1

Type RM Length L Ch R = 1 ,241     ,47.2,50.5,53.8
XS GIS Cut Line= 3
2145859.84624953645015.4788585732145865.78904324645085.878107082
2145932.07404995645189.648427938
#Sta/Elev= 30
       0 1121.51     3.9 1120.21     9.3 1118.89    17.8 1117.51    35.2 1116.15
    45.9 1115.81    49.9 1115.28    57.9  1113.6    65.9  1113.1    69.9 1112.12
    75.1 1111.31    77.7  1110.4    84.1 1107.45    89.2 1105.43    93.6 1104.64
    97.9 1104.44   104.8  1104.7   112.5 1106.63   117.3 1108.95   126.9 1115.19
   131.5 1117.31   135.6 1118.53   147.2 1120.41   156.8 1120.64   164.6  1121.3
   171.7 1122.83   179.1 1124.92   183.7 1126.69   188.5 1127.97   193.8 1127.89
#Mann= 4 ,-1,0
       0      .1       0    93.6    .045       0   104.8      .1       0
  140.65     .08       0
Bank Sta=93.6,104.8
XS Rating Curve= 0 ,0
Exp/Cntr(USF)=0,0
Exp/Cntr=0.3,0.1

Type RM Length L Ch R = 1 ,191     ,59.2,56.3,53.1
XS GIS Cut Line= 5
2145836.52515718645009.9714218692145825.04442729645041.450200428
2145831.10754427645110.5843784072145848.07863262645173.061814007
2145890.18605425645235.575592111
#Sta/Elev= 30
       0 1125.95    20.4 1122.51    37.3 1119.37    41.3 1118.25    49.3 1115.39
    61.3 1112.65    69.4 1111.41    89.4 1110.39   102.6 1108.58   113.9 1105.52
   118.9 1103.33   122.2 1101.56   126.3 1100.41   128.7 1100.37   130.5  1100.4
   134.6 1101.53   142.9 1104.29     147 1104.97   151.2 1104.95   155.3 1105.88
   159.5 1107.75   167.7    1112   172.6  1113.1   182.3 1114.13   190.9 1114.45
   206.4 1113.61   210.8 1113.64     237 1115.34   240.1 1115.66     243 1116.32
#Mann= 3 ,-1,0
       0      .1       0   122.2    .045       0   134.6      .1       0
Bank Sta=122.2,134.6
XS Rating Curve= 0 ,0
Exp/Cntr(USF)=0,0
Exp/Cntr=0.3,0.1

Type RM Length L Ch R = 1 ,134     ,40,39.8,40
XS GIS Cut Line= 5
2145801.30364955645014.7909416182145786.94959585645052.624684319
2145780.96391346645149.9829454782145821.07881811645215.169665541
2145848.83904847645250.691413613
#Sta/Elev= 30
       0 1123.22    14.5 1121.19    32.5 1119.19    36.8 1118.38    43.6 1116.07
    57.1 1110.23    58.7 1110.02    73.1  1109.1    85.1 1107.45    93.1 1106.73
   101.1 1107.15   109.1 1106.86   113.2 1106.49   121.2 1105.01   129.2 1105.72
   133.2 1105.74   139.8 1103.97   146.5 1100.44   151.11098.519   157.2 1097.55
   160.5 1097.72   165.2 1098.53   174.7 1100.04   179.3 1101.76   182.3 1103.23
   188.7 1107.34   192.1 1108.58   197.6  1109.7   222.2 1110.56   259.6 1112.65
#Mann= 4 ,-1,0
       0      .1       0   151.1    .045       0   165.2      .1       0
  244.55     .06       0
Bank Sta=151.1,165.2
XS Rating Curve= 0 ,0
Exp/Cntr(USF)=0,0
Exp/Cntr=0.3,0.1

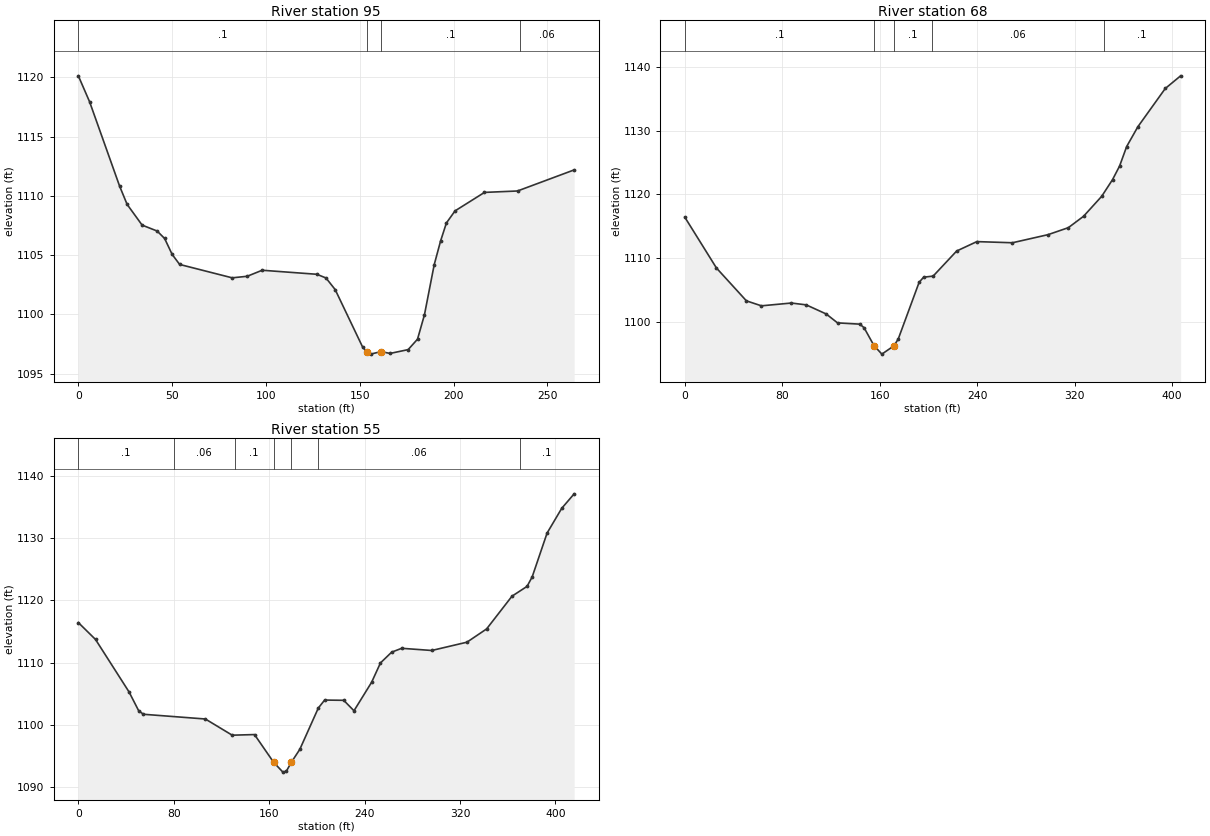
Type RM Length L Ch R = 1 ,95      ,25.6,27.1,24
XS GIS Cut Line= 4
2145736.41899565645035.1357915982145736.87613363645156.277355592
2145779.38996552645217.0767065782145839.27504055645251.362054878
#Sta/Elev= 30
       0 1120.14       6 1117.95      22 1110.83      26 1109.29      34 1107.54
      42 1107.04      46 1106.41      50 1105.07      54 1104.22      82 1103.09
      90 1103.22      98 1103.73   127.1 1103.39     132 1103.08   136.9  1102.1
   151.5 1097.26  153.65 1096.85   155.8 1096.65   161.3 1096.86   166.2 1096.71
   175.8 1097.03   180.8 1097.91   184.5 1099.97   189.7  1104.2   193.1  1106.2
   196.2 1107.72   200.8 1108.74   216.5  1110.3   234.1 1110.42   264.3  1112.2
#Mann= 4 ,-1,0
       0      .1       0  153.65    .045       0   161.3      .1       0
  235.33     .06       0
Bank Sta=153.65,161.3
XS Rating Curve= 0 ,0
Exp/Cntr(USF)=0,0
Exp/Cntr=0.3,0.1

Type RM Length L Ch R = 1 ,68      ,14.6,12.5,11.2
XS GIS Cut Line= 5
2145704.38818273645055.7327966032145732.69475485645185.376653409
2145773.79603039645243.5108899862145907.96966074645283.375899733
2145962.41131706645315.611090973
#Sta/Elev= 30
       0  1116.4      26 1108.41    50.6 1103.25    62.9 1102.47    87.5 1102.91
    99.7 1102.62   116.1 1101.19   125.4 1099.79   143.7 1099.59   147.2 1099.03
   155.31096.231   161.8 1094.88   171.6 1096.17   175.2 1097.23   192.4 1106.17
   196.1 1106.97   203.9 1107.14   223.2 1111.08   239.8 1112.56     269 1112.38
   298.2 1113.65   314.9 1114.75   327.4 1116.54   342.3 1119.68   351.2  1122.3
     357 1124.44   362.8  1127.5     372 1130.61   394.5 1136.62   407.1 1138.61
#Mann= 5 ,-1,0
       0      .1       0   155.3    .045       0   171.6      .1       0
   202.7     .06       0  343.87      .1       0
Bank Sta=155.3,171.6
XS Rating Curve= 0 ,0
Exp/Cntr(USF)=0,0
Exp/Cntr=0.3,0.1

Type RM Length L Ch R = 1 ,55      ,,,
XS GIS Cut Line= 4
2145695.66657868645058.7402909272145698.25855102 645169.82481942
2145777.49884801645259.0627239752145953.75296655645316.086115268
#Sta/Elev= 30
       0 1116.42    14.4 1113.71    42.5 1105.29    50.5  1102.3    54.5  1101.7
   106.5 1100.94     129 1098.34   147.7 1098.44   163.7    1094   171.5 1092.41
   174.4 1092.56   178.71094.022   185.7 1096.07   201.2  1102.7   206.5 1103.98
   222.5 1103.94   231.1 1102.26   245.9 1106.84   253.3 1109.94   262.7 1111.67
   271.1 1112.29   296.3 1111.94   325.8 1113.27   342.3  1115.4   363.6 1120.66
   376.2 1122.23   380.5 1123.75     393 1130.79   405.3 1134.77   415.7 1137.09
#Mann= 7 ,-1,0
       0      .1       0      80     .06       0  131.11      .1       0
   163.7    .045       0   178.7      .1       0  201.11     .06       0
  370.46      .1       0
Bank Sta=163.7,178.7
XS Rating Curve= 0 ,0
Exp/Cntr(USF)=0,0
Exp/Cntr=0.3,0.1
LCMann Table=0

Chan Stop Cuts=-1
Use User Specified Reach Order=0
Composite Channel Slope=5